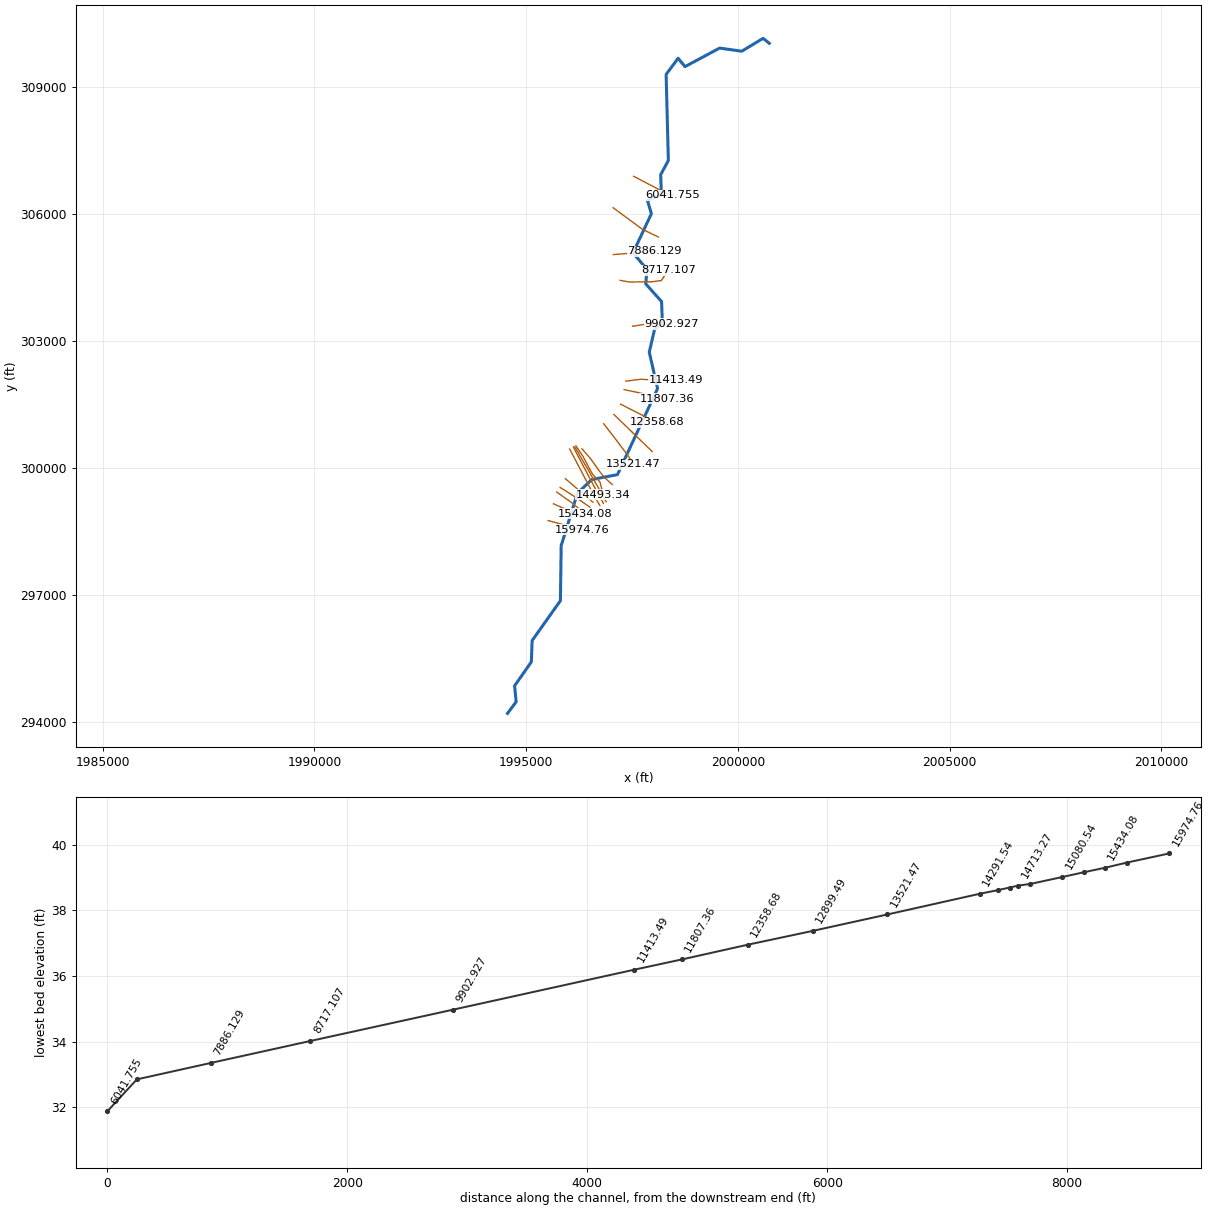
--- US278overBeaver.prj (project) ---

Proj Title=US 278 over Beaver Dam Cr_Prelim
Current Plan=p03
Default Exp/Contr=0.3,0.1
English Units
Geom File=g02
Geom File=g03
Geom File=g01
Geom File=g04
Geom File=g05
Geom File=g06
Geom File=g07
Flow File=f01
Flow File=f02
Plan File=p02
Plan File=p03
Plan File=p01
Plan File=p04
Plan File=p05
Plan File=p07
Plan File=p06
Plan File=p08
Y Axis Title=Elevation
X Axis Title(PF)=Main Channel Distance
X Axis Title(XS)=Station
BEGIN DESCRIPTION:
END DESCRIPTION:
DSS File=dss
DSS Export Rating Curves= 0
DSS Export Rating Curve Sorted= 0
DSS Export Volume Flow Curves= 0
DXF OffsetX= 0
DXF OffsetY= 0
DXF ScaleX= 1
DXF ScaleY= 10

--- US278overBeaver.p03 (plan) ---

Plan Title=Existing Conditions
Program Version=6.50
Short Identifier=Existing Conditions
Geom File=g03
Flow File=f01
Subcritical Flow
K Sum by GR= 0
Std Step Tol= 0.01
Critical Tol= 0.01
Num of Std Step Trials= 20
Max Error Tol= 0.3
Flow Tol Ratio= 0.001
Split Flow NTrial= 30
Split Flow Tol= 0.02
Split Flow Ratio= 0.02
Log Output Level= 0
Friction Slope Method= 1
Unsteady Friction Slope Method= 2
Unsteady Bridges Friction Slope Method= 1
Parabolic Critical Depth
Global Vel Dist= 0 , 0 , 0
Global Log Level= 0
CheckData=True
Encroach Param=-1 ,0,0, 0
Flow Ratio Tolerance=0.1
Flow Ratio Min Ratio=0.5
Flow Ratio Max Ratio=4
Flow Ratio Max Iterations= 10
Computation Interval=1MIN
Output Interval=1HOUR
Instantaneous Interval=1HOUR
Mapping Interval=1HOUR
Computation Time Step Use Courant=        0
Computation Time Step Use Time Series=    0
Computation Time Step Count To Double=0
Computation Time Step Max Doubling=0
Computation Time Step Max Halving=0
Computation Time Step Residence Courant=0
Run HTab= 0
Run UNet= 0
Run Sediment= 0
Run PostProcess= 0
Run WQNet= 0
Run RASMapper= 0
UNET Theta= 1
UNET Theta Warmup= 1
UNET ZTol= 0.02
UNET ZSATol= 0.02
UNET MxIter= 20
UNET Max Iter WO Improvement= 0
UNET MaxInSteps= 0
UNET DtIC= 0
UNET DtMin= 0
UNET MaxCRTS= 20
UNET WFStab= 2
UNET SFStab= 1
UNET WFX= 1
UNET SFX= 1
UNET Gravity=32.17405
UNET 1D Methodology=Finite Difference
UNET DSS MLevel= 4
UNET Pardiso=0
UNET DZMax Abort= 100
UNET Use Existing IB Tables=-1
UNET Froude Reduction=False
UNET Froude Limit= 0.8
UNET Froude Power= 4
UNET D1 Cores= 0
UNET WindReference=Eulerian
UNET WindDragFormulation=Hsu (1988)
UNET D2 Coriolis=0
UNET D2 Cores= 0
UNET D2 Theta= 1
UNET D2 Theta Warmup= 1
UNET D2 Z Tol= 0.01
UNET D2 Volume Tol= 0.01
UNET D2 Max Iterations= 20
UNET D2 Equation= 0
UNET D2 RampUpFraction=0.1
UNET D2 TimeSlices= 1
UNET D2 Turbulence Formulation=None
UNET D2 Eddy Viscosity=0.3
UNET D2 Transverse Eddy Viscosity=0.1
UNET D2 Smagorinsky Mixing=0.05
UNET D2 BCVolumeCheck=0
UNET D2 Cores=0
UNET D2 SolverType=PARDISO (Direct)
UNET D2 Minimum Iterations= 3
UNET D2 Maximum Iterations= 30
UNET D2 Restart Number= 10
UNET D2 Relaxation Coeff=1.3
UNET D2 SOR Precondition Iterations= 10
UNET D2 ILUT Maximum Fill= 8
UNET D2 ILUT Tolerance=1E-08
UNET D2 Convergence Tolerance=0.00001
PS Theta= 1
PS WS Tol= 0.01
PS Volume Tol= 0.01
PS Max Iterations= 20
PS Time Slices= 1
PS Iterate With 2D=0
PS Cores=0
UNET D1D2 MaxIter= 0
UNET D1D2 ZTol=0.01
UNET D1D2 QTol=0.1
UNET D1D2 MinQTol=1
DSS File=dss
Write IC File= 0
Write IC File at Fixed DateTime=0
Write IC File at Sim End=0
Echo Input=False
Echo Parameters=False
Echo Output=False
Write Detailed= 0
HDF Write Warmup=0
HDF Write Time Slices=0
HDF Flush=0
HDF Compression= 1
HDF Chunk Size= 1
HDF Spatial Parts= 1
HDF Use Max Rows=0
HDF Fixed Rows= 1
Calibration Method= 0
Calibration Iterations= 20
Calibration Max Change=0.05
Calibration Tolerance=0.2
Calibration Maximum=1.5
Calibration Minimum=0.5
Calibration Optimization Method= 1
WQ AD Non Conservative
WQ ULTIMATE=-1
WQ Max Comp Step=1HOUR
WQ Output Interval=15MIN
WQ Output Selected Increments= 0
WQ Create Restart=0
WQ Fixed Restart=0
WQ System Summary=0
WQ Write To DSS=0
Sorting and Armoring Iterations= 10
XS Update Threshold= 0.02
Bed Roughness Predictor= 0
Hydraulics Update Threshold= 0.02
Energy Slope Method= 1
Volume Change Method= 1
Sediment Retention Method= 0
Sediment TS Multiplier= 1
Warm Up Method= 0
XS Weighting Method= 0
Number of US Weighted Cross Sections= 1
Number of DS Weighted Cross Sections= 1
Upstream XS Weight=0
Main XS Weight=1
Downstream XS Weight=0
Number of DS XS's Weighted with US Boundary= 1
Upstream Boundary Weight= 1
Weight of XSs Associated with US Boundary= 0
Number of US XS's Weighted with DS Boundary= 1
Downstream Boundary Weight= 0.5
Weight of XSs Associated with DS Boundary= 0.5
Percentile Method= 0
Sediment Output Level= 3
Mass or Volume Output= 0
Output Increment Type= 1
Profile and TS Output Increment= 1
Transport Output Increment 1
XS Output Flag= 0
XS Output Increment= 10
Read HDF5 Sediment Hotstart= 0
Sediment Hotstart Type= 0
Write Gradation File= 0
Read Gradation Hotstart= 0
Write HDF5 File= 1
Write Binary Output= 1
Write DSS Sediment File= 0
DSS Sediment Output Type= 1
SV Curve= 0
Specific Gage Flag= 0
Subcell Erosion Methods= 0
Subcell Deposition Methods= 0
Advection Scheme= 1
Matrix Solver= 0
Implicit Weighting Factor= 1
Maximum Outer Loop Convergence Iterations= 5
Convergence Maximum Absolute= 0.001
Convergence RMSE= 0.0001
Grain Fractions Max Abs Error= 0.001
Max Subgrid Regions= 1
Max Subgrid Length Scale= 3.402823E+38
Initial Layer Thickness= 3
Min Layer Thickness= 0.1
Max Layer Thickness= 6
Number of Layers= 5

--- US278overBeaver.p01 (plan) ---

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Plan Title=Natural Conditions
Short Identifier=Natural Conditions
Geom File=g01
Flow File=f01

--- US278overBeaver.p02 (plan) ---

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Plan Title=Natural Conditions-ROUGH
Short Identifier=NATURAL CONDITIONS-ROUGH
Geom File=g02
Flow File=f01

--- US278overBeaver.p04 (plan) ---

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Plan Title=Proposed 120ft_TypeIII
Short Identifier=Prop 120'_Type-III
Geom File=g04
Flow File=f01

--- US278overBeaver.p05 (plan) ---

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Plan Title=Proposed_Culverts_2-Double 10x10
Short Identifier=Prop-Culv_2 Double10x10
Geom File=g05
Flow File=f01

--- US278overBeaver.p06 (plan) ---

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Plan Title=Natural Convergence - 100yr
Short Identifier=Natural Convergence 100yr
Geom File=g01
Flow File=f02

--- US278overBeaver.p07 (plan) ---

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Plan Title=Proposed_Culverts_2-Double 10x12
Short Identifier=Prop 2-Double 10x12
Geom File=g06
Flow File=f01

--- US278overBeaver.p08 (plan) ---

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Plan Title=Prop_2x10x8 + 2x10x12
Short Identifier=Prop_2x10x8 + 2x10x12
Geom File=g07
Flow File=f01

--- US278overBeaver.f01 (steady flow) ---

Flow Title=US 278 Beaver Dam Creek flows_USGS RREs
Program Version=6.50
Number of Profiles= 7
Profile Names=Q2yr (50%AEP),Q10yr (10%),Q25yr (4%),Q50yr (2% ),Q100yr (1.0%AEP),Q200yr (0.5%AEP),Q500yr (0.2%AEP)
River Rch & RM=Beaver Dam Creek,Reach 1         ,15974.76
     300     815    1160    1470    1790    2130    2600
Boundary for River Rch & Prof#=Beaver Dam Creek,Reach 1         , 1
Up Type= 0
Dn Type= 3
Dn Slope=0.0013
Boundary for River Rch & Prof#=Beaver Dam Creek,Reach 1         , 2
Up Type= 0
Dn Type= 3
Dn Slope=0.0013
Boundary for River Rch & Prof#=Beaver Dam Creek,Reach 1         , 3
Up Type= 0
Dn Type= 3
Dn Slope=0.0013
Boundary for River Rch & Prof#=Beaver Dam Creek,Reach 1         , 4
Up Type= 0
Dn Type= 3
Dn Slope=0.0013
Boundary for River Rch & Prof#=Beaver Dam Creek,Reach 1         , 5
Up Type= 0
Dn Type= 3
Dn Slope=0.0013
Boundary for River Rch & Prof#=Beaver Dam Creek,Reach 1         , 6
Up Type= 0
Dn Type= 3
Dn Slope=0.0013
Boundary for River Rch & Prof#=Beaver Dam Creek,Reach 1         , 7
Up Type= 0
Dn Type= 3
Dn Slope=0.0013
DSS Import GetInterval= 0
DSS Import GetPeak= 0
DSS Import FillOption= 0

--- US278overBeaver.f02 (steady flow) ---

Flow Title=Natural-Convergence_100yr USGS RREs
Program Version=6.50
Number of Profiles= 7
Profile Names=Norm(100yr) + 3,Norm(100yr) + 2,Norm(100yr) + 1,Normal(100yr),Norm(100yr) - 1,Norm(100yr) - 2,Norm(100yr) - 3
River Rch & RM=Beaver Dam Creek,Reach 1         ,15974.76
    1790    1790    1790    1790    1790    1790    1790
Boundary for River Rch & Prof#=Beaver Dam Creek,Reach 1         , 1
Up Type= 0
Dn Type= 1
Dn Known WS=40.4
Boundary for River Rch & Prof#=Beaver Dam Creek,Reach 1         , 2
Up Type= 0
Dn Type= 1
Dn Known WS=39.7
Boundary for River Rch & Prof#=Beaver Dam Creek,Reach 1         , 3
Up Type= 0
Dn Type= 1
Dn Known WS=38.7
Boundary for River Rch & Prof#=Beaver Dam Creek,Reach 1         , 4
Up Type= 0
Dn Type= 1
Dn Known WS=37.7
Boundary for River Rch & Prof#=Beaver Dam Creek,Reach 1         , 5
Up Type= 0
Dn Type= 1
Dn Known WS=36.7
Boundary for River Rch & Prof#=Beaver Dam Creek,Reach 1         , 6
Up Type= 0
Dn Type= 1
Dn Known WS=35.7
Boundary for River Rch & Prof#=Beaver Dam Creek,Reach 1         , 7
Up Type= 0
Dn Type= 1
Dn Known WS=34.7
DSS Import GetInterval= 0
DSS Import GetPeak= 0
DSS Import FillOption= 0

--- US278overBeaver.g03 (geometry) ---

Geom Title=Existing Conditions
Program Version=6.50

River Reach=Beaver Dam Creek,Reach 1
Reach XY= 30
      1994561.28       294210.94      1994765.57       294483.33
      1994728.91       294860.49       1995124.4       295426.23
      1995142.73       295929.11      1995810.62         296872.
      1995828.95       298171.11      1996211.35       299407.35
      1996551.84       299732.12      1997156.87       299847.37
        1998105.       301879.83      1997908.56       302738.92
      1998034.28       303281.08      1998217.63       303430.38
      1998199.29       303933.25      1997824.75       304352.32
      1997856.18       304687.57      1997526.17       305085.68
      1997958.33       306007.63      1997866.66       306319.31
      1998194.05        306468.6      1998178.34       306929.57
      1998359.06       307264.82      1998306.68       309297.29
      1998589.55       309677.07      1998751.93       309480.63
      1999569.11       309918.03      2000092.94       309844.69
      2000595.82       310148.52      2000742.49       310030.65

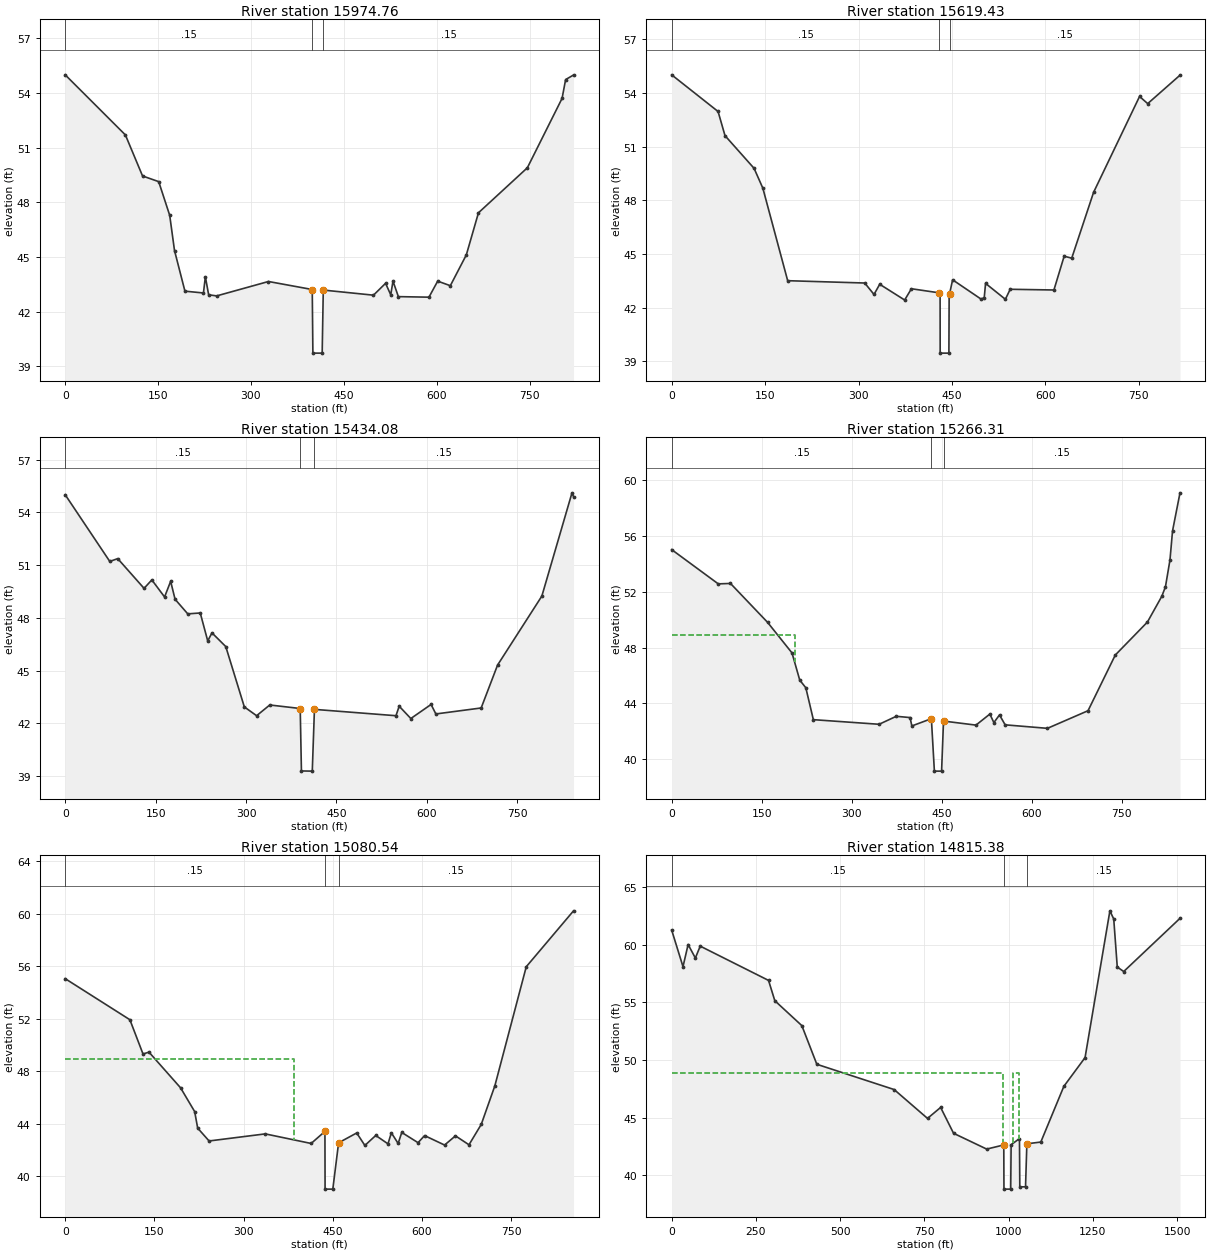
Type RM Length L Ch R = 1 ,15974.76,370,355.33,340
XS GIS Cut Line= 6
      1995520.95       298763.35      1996209.87       298577.81
      1996216.18        298576.1      1996218.86       298575.39
      1996261.44       298563.91      1996313.63       298549.86
#Sta/Elev= 30
       0      55   97.23    51.7  124.91   49.45  150.98   49.14  168.76   47.29
  176.51   45.36  193.36   43.13  223.26   43.03  226.34   43.92  231.67   42.93
  244.61   42.87  328.28   43.66  398.96   43.22     400   39.73     415   39.73
  416.78   43.19  497.83   42.91  517.37   43.56  525.73   42.93  529.36   43.68
  538.04   42.83  587.45    42.8  601.54   43.68  621.96   43.43   647.8   45.12
  667.39   47.43  746.36    49.9  802.44   53.71  808.16   54.74  820.93   54.99
#Mann= 3 ,-1,0
       0     .15       0  398.96     .08       0  416.78     .15       0
Bank Sta=398.96,416.78
XS Rating Curve= 0 ,0
Exp/Cntr=0.3,0.1

Type RM Length L Ch R = 1 ,15619.43,210,185.35,150
XS GIS Cut Line= 6
      1995645.63       299159.32      1996043.66       298984.54
      1996048.88       298982.26      1996058.53       298978.01
      1996105.04        298957.6      1996392.75       298831.26
#Sta/Elev= 30
       0   55.01   74.47   52.96   85.61   51.61  132.31   49.78  146.37   48.67
  186.22    43.5  309.91   43.37  324.79   42.73  333.94    43.3  373.99   42.42
  384.84   43.05  429.61   42.82  430.88   42.74     431   39.45     445   39.45
   445.4   42.64  446.07   42.76  450.96   43.55  496.68   42.47  501.74   42.55
  503.85   43.35  535.66   42.46  543.39   43.02  613.59   42.98  630.03   44.87
  642.18   44.76  677.26   48.44  751.06    53.8  764.13    53.4  815.97   54.99
#Mann= 3 ,-1,0
       0     .15       0  429.61     .08       0  446.07     .15       0
Bank Sta=429.61,446.07
XS Rating Curve= 0 ,0
Exp/Cntr=0.3,0.1

Type RM Length L Ch R = 1 ,15434.08,145,167.76,160
XS GIS Cut Line= 6
       1995723.1       299437.56      1996074.88       299187.75
      1996275.53       299017.88      1996279.15        299014.8
      1996346.01       298958.21      1996389.38       298921.48
#Sta/Elev= 30
       0      55   73.97   51.21   87.17   51.37  130.85   49.68  143.76   50.16
   164.9   49.19  174.98   50.08  182.31   49.06  203.35   48.23  224.11   48.28
  236.51   46.69  243.54   47.15  266.46   46.37  297.25   42.94  317.62   42.44
  339.45   43.05  389.98   42.85     392    39.3     410   39.29  413.59    42.8
  548.87   42.44  554.23   42.98  573.54   42.28  607.14   43.08  615.08   42.54
  690.26   42.88   717.5   45.32  790.97   49.24  840.99   55.11  843.54   54.89
#Mann= 3 ,-1,0
       0     .15       0  389.98     .08       0  413.59     .15       0
Bank Sta=389.98,413.59
XS Rating Curve= 0 ,0
Exp/Cntr=0.3,0.1

Type RM Length L Ch R = 1 ,15266.31,185,185.78,160
XS GIS Cut Line= 6
      1995802.76       299546.81      1995818.88       299536.57
      1995819.54       299536.14      1995850.85       299516.26
       1996190.1        299300.7       1996508.8        299078.4
#Sta/Elev= 30
       0      55   77.67   52.55   98.05   52.58  159.88    49.8  200.65   47.61
  213.51   45.67  223.67   45.12   236.2   42.84  345.87   42.51  374.48   43.08
  397.45   42.99  400.41   42.39  432.98   42.91     438   39.16     450   39.16
  453.22   42.74  507.33   42.45  530.48   43.24  537.18   42.63  546.56   43.18
  555.96   42.47  626.49   42.22  694.16   43.48  739.58   47.46  793.18   49.82
  817.15   51.66  823.23   52.34  830.78   54.26  835.06   56.34  847.49   59.06
#Mann= 3 ,-1,0
       0     .15       0  432.98     .08       0  453.22     .15       0
#XS Ineff= 2 , 0
             205    48.9
Permanent Ineff=
       F       F
Bank Sta=432.98,453.22
XS Rating Curve= 0 ,0
Exp/Cntr=0.5,0.3

Type RM Length L Ch R = 1 ,15080.54,300,265.15,200
XS GIS Cut Line= 6
       1995928.8        299751.4      1996262.01       299467.02
       1996349.5       299392.37      1996380.11       299366.23
      1996397.66       299351.27        1996579.        299196.5
#Sta/Elev= 30
       0   55.05  108.76   51.92  130.83   49.31  140.91   49.45  194.01   46.73
  217.69   44.92  222.76   43.66  241.94   42.68  336.42   43.22  413.55   42.49
  436.75   43.41     437   39.01     450   39.01  459.73   42.54  490.17   43.29
   503.9   42.34  522.22    43.1  542.77   42.46  548.45    43.3  559.89   42.49
  565.94   43.33  593.33   42.55  604.34   43.09  637.94   42.37  656.26   43.07
  678.98   42.39  699.58   43.94  722.46   46.88  775.31   55.96  854.79   60.22
#Mann= 3 ,-1,0
       0     .15       0  436.75     .08       0  459.73     .15       0
#XS Ineff= 2 , 0
             385    48.9
Permanent Ineff=
       F       F
Bank Sta=436.75,459.73
XS Rating Curve= 0 ,0
Exp/Cntr=0.5,0.3

Type RM Length L Ch R = 1 ,14815.38,100,102.11,100
XS GIS Cut Line= 6
       1996029.1        300452.3       1996418.2        299711.1
       1996585.8        299387.3      1996615.49       299336.45
      1996628.47       299314.25       1996740.8        299121.9
#Sta/Elev= 30
       0   61.25   33.61   58.08   48.76      60   70.29   58.83   84.72   59.86
  287.42   56.89  306.07   55.13  386.26   52.97  430.73   49.62  660.18   47.43
  759.16   44.93  798.09   45.88  836.43   43.64  934.77   42.27  985.49   42.63
     986    38.8    1006    38.8 1007.28   42.65 1032.02   43.18    1033      39
    1050      39 1053.97   42.73 1095.35   42.88 1163.77   47.71 1226.66    50.2
 1300.36   62.92 1311.77   62.21 1322.22   58.05 1341.36   57.66 1508.37   62.27
#Mann= 3 ,-1,0
       0     .15       0  985.49     .08       0 1053.97     .15       0
#XS Ineff= 3 ,-1
       0     982    48.9    1014    1030    48.9    1200    1502    48.9
Permanent Ineff=
       F       F       F
Bank Sta=985.49,1053.97
XS Rating Curve= 0 ,0
Exp/Cntr=0.5,0.3

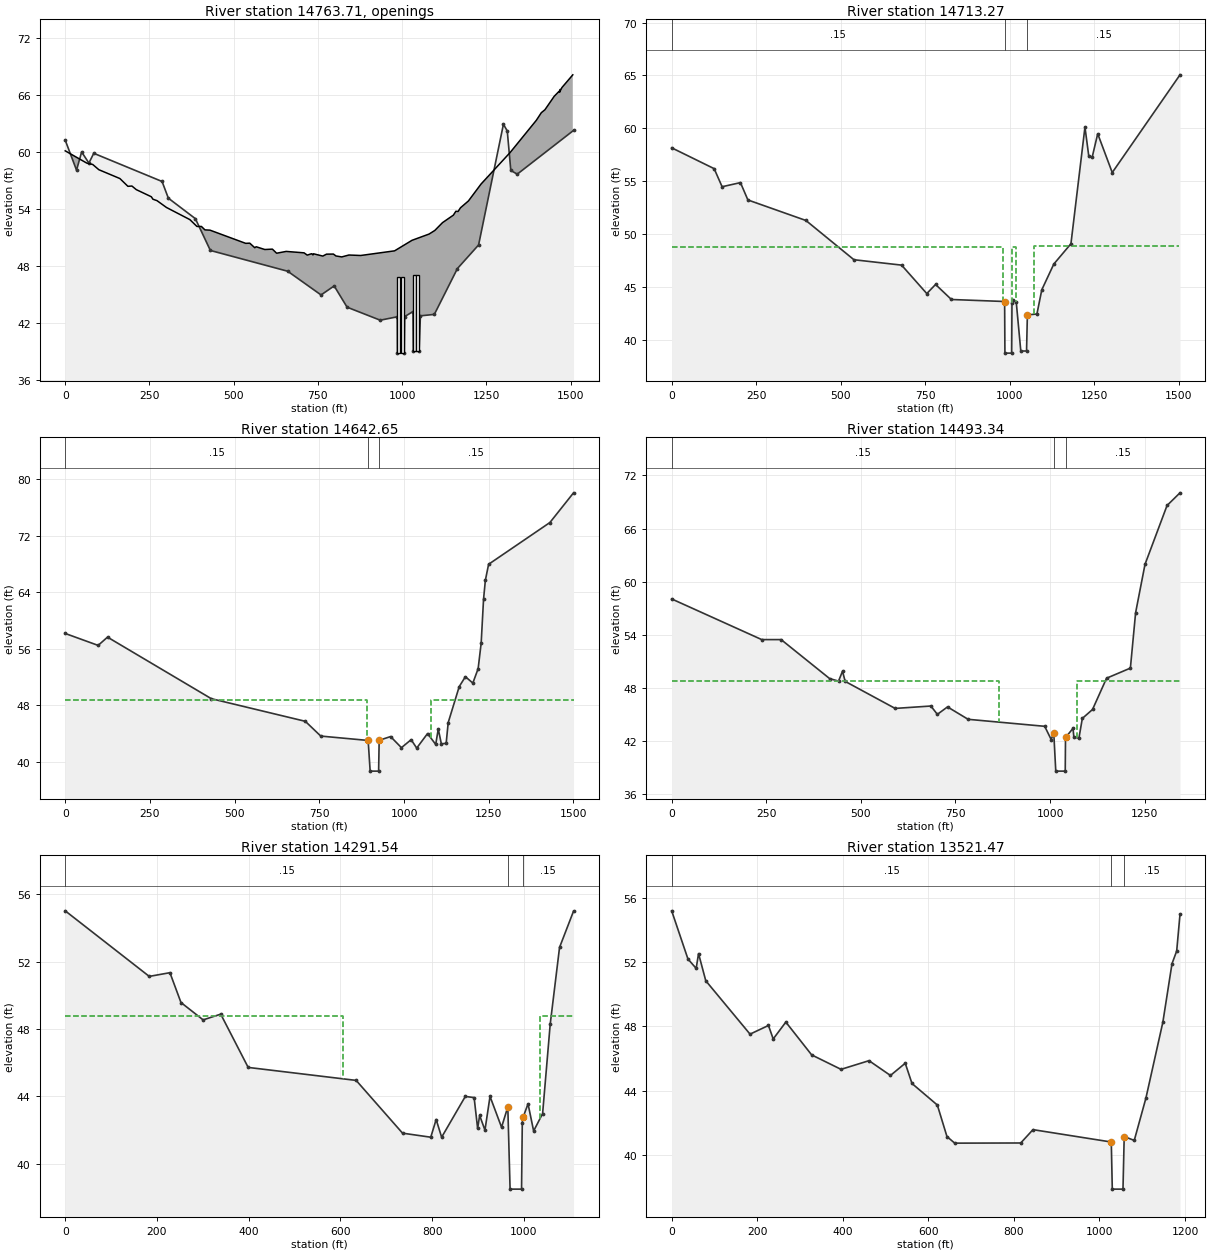
Type RM Length L Ch R = 4 ,14763.71,,,
Bridge Culvert--1,0,-1,-1, 0
Deck Dist Width WeirC Skew NumUp NumDn MinLoCord MaxHiCord MaxSubmerge Is_Ogee
32,30,2.6,0, 60, 60, , , 0.98, 0, 0,0,,
       0   63.78    81.7   99.81  162.22  186.05  197.95  210.94  255.53  260.33
  272.37  300.48  369.93  390.87  404.19  414.57  429.67   535.5  547.58  562.45
  566.78  592.29  614.78  627.37  655.63  708.77  718.15  731.21  735.25  736.79
  764.32  775.26  795.89  803.45  820.64  841.84  876.75  977.36 1029.02 1079.76
 1096.75 1119.48 1151.72  1159.2 1165.72 1172.95 1196.52 1233.91 1320.17 1398.01
 1412.77 1423.47 1451.06 1465.93 1467.23 1468.18 1468.69 1469.53 1473.91 1506.19
   60.12   58.83   58.68   58.13    57.2   56.38   56.41   56.03   55.28   55.02
   54.87   54.15   52.87   52.15   52.15   51.79   51.76   50.37   50.39   49.91
   50.01   49.72   49.76   49.33   49.52   49.37   49.13   49.28   49.15   49.27
   49.03   49.23   49.24   49.04   48.94   49.14   49.09   49.58   50.69   51.35
   51.73   52.55   53.34   53.75   53.73   54.12   54.84   56.62   59.94   63.34
   64.14   64.45   65.87   66.41    66.3   66.35   66.59   66.49   66.79   68.13
                                                                                
                                                                                
                                                                                
                                                                                
                                                                                
                                                                                
       0   63.78    81.7   99.81  162.22  186.05  197.95  210.94  255.53  260.33
  272.37  300.48  369.93  390.87  404.19  414.57  429.67   535.5  547.58  562.45
  566.78  592.29  614.78  627.37  655.63  708.77  718.15  731.21  735.25  736.79
  764.32  775.26  795.89  803.45  820.64  841.84  876.75  977.36 1029.02 1079.76
 1096.75 1119.48 1151.72  1159.2 1165.72 1172.95 1196.52 1233.91 1320.17 1398.01
 1412.77 1423.47 1451.06 1465.93 1467.23 1468.18 1468.69 1469.53 1473.91 1506.19
   60.12   58.83   58.68   58.13    57.2   56.38   56.41   56.03   55.28   55.02
   54.87   54.15   52.87   52.15   52.15   51.79   51.76   50.37   50.39   49.91
   50.01   49.72   49.76   49.33   49.52   49.37   49.13   49.28   49.15   49.27
   49.03   49.23   49.24   49.04   48.94   49.14   49.09   49.58   50.69   51.35
   51.73   52.55   53.34   53.75   53.73   54.12   54.84   56.62   59.94   63.34
   64.14   64.45   65.87   66.41    66.3   66.35   66.59   66.49   66.79   68.13
                                                                                
                                                                                
                                                                                
                                                                                
                                                                                
                                                                                
BR Coef=-1 , 0 , 0 ,, 0 ,,,0.8,-1,,0,
WSPro=,,,, 1 ,,,, 0 ,,,, 0 ,,,,-1 ,-1 ,-1 , 0 , 0 , 0 , 0 , 0
Multiple Barrel Culv=2,8,10,36,0.013,0.4,1,8,1,38.8,38.75, 2,Culvert #1  , 0 ,32
   989.5  989.54 1000.56  1000.5
BC Culvert Barrel=1,Barrel #1,0
BC Culvert Barrel=2,Barrel #2,0
Culvert Bottom n=0.013
Multiple Barrel Culv=2,8,8,36,0.013,0.4,1,8,1,39,38.95, 2,Culvert #2  , 0 ,32
  1036.5  1036.5  1045.5  1045.5
BC Culvert Barrel=1,Barrel #1,0
BC Culvert Barrel=2,Barrel #2,0
Culvert Bottom n=0.013
BC Mult= 2 ,0,1030.15,0,1030.15
BC Mult= 2 ,1009.11,1508.37,1009.11,1508.37
BC Design=,, 0 ,, 0 ,,,,,,
BC Use User HTab Curves=0
BC User HTab FreeFlow(D)= 0

Type RM Length L Ch R = 1 ,14713.27,70,70.62,80
XS GIS Cut Line= 6
       1996117.9        300498.9       1996334.9        300080.2
       1996482.6        299802.5      1996575.68       299626.62
       1996672.1        299444.4       1996826.3        299172.3
#Sta/Elev= 30
       0   58.16  125.69   56.19  149.21   54.48  203.48   54.87  225.54   53.23
  397.23   51.29  539.23   47.58  680.28   47.07  754.84   44.38  780.77   45.24
  827.69   43.82  985.12   43.63     986   38.75    1006   38.75 1006.88   43.49
 1009.07   43.76 1019.51   43.58    1033   38.95    1050   38.95 1052.46   42.36
 1080.72   42.45 1095.14   44.74 1130.66   47.17 1181.34   49.09 1222.82   60.12
 1234.19   57.36 1244.15   57.27 1260.57   59.49 1303.56   55.82 1504.03   65.06
#Mann= 3 ,-1,0
       0     .15       0  985.12     .08       0 1052.46     .15       0
#XS Ineff= 3 ,-1
       0     980    48.8  1006.9    1019    48.8    1072    1500    48.9
Permanent Ineff=
       F       F       F
Bank Sta=985.12,1052.46
XS Rating Curve= 0 ,0
Exp/Cntr=0.5,0.3

Type RM Length L Ch R = 1 ,14642.65,75,100,80
XS GIS Cut Line= 6
       1996144.3        300506.6       1996178.5        300455.9
        1996520.        299864.2       1996797.7        299378.3
      1996798.91       299376.09       1996892.4        299206.4
#Sta/Elev= 30
       0   58.17   97.19   56.48  124.85   57.65  431.24   48.94   708.6   45.74
  754.25   43.65  894.11   43.03     900   38.69     925   38.69  926.61   43.05
  960.26   43.58   992.3   42.01 1020.97   43.14  1037.4   41.95 1069.45   44.01
  1093.5   42.46 1101.03   44.65 1110.09   42.56 1124.35   42.62 1130.35   45.56
 1162.88   50.65  1181.1   52.05 1203.06   51.15 1218.72   53.19 1227.64   56.79
 1234.65      63 1240.05    65.7 1249.62   67.96 1430.59   73.87 1500.25   78.07
#Mann= 3 ,-1,0
       0     .15       0  894.11     .08       0  926.61     .15       0
#XS Ineff= 2 , 0
             890    48.8    1080            48.8
Permanent Ineff=
       F       F
Bank Sta=894.11,926.61
XS Rating Curve= 0 ,0
Exp/Cntr=0.5,0.3

Type RM Length L Ch R = 1 ,14493.34,165,150,200
XS GIS Cut Line= 6
       1996175.6         300528.       1996340.1        300284.1
        1996567.        299861.2      1996729.96       299689.61
       1996744.7        299674.1       1996822.2        299372.8
#Sta/Elev= 30
       0   58.05  237.96   53.46  289.24   53.46  417.35   49.06  440.92   48.77
  451.47   49.89  458.48   48.74  590.54   45.69  684.92   45.96   702.1   45.02
  728.91   45.86  783.38   44.46  985.74   43.67 1002.81   42.18 1009.67   42.93
    1015   38.61    1040   38.61 1040.73   42.41 1041.18   42.42  1060.5   43.44
 1062.86   42.43 1076.23   42.34 1085.14   44.56 1112.13   45.57 1149.19    49.1
 1212.16   50.24 1225.98    56.5 1250.83   61.96 1309.03    68.6 1343.26   70.03
#Mann= 3 ,-1,0
       0     .15       0 1009.67     .08       0 1041.18     .15       0
#XS Ineff= 2 , 0
             865    48.8    1070            48.8
Permanent Ineff=
       F       F
Bank Sta=1009.67,1041.18
XS Rating Curve= 0 ,0
Exp/Cntr=0.5,0.3

Type RM Length L Ch R = 1 ,14291.54,775,770.07,725
XS GIS Cut Line= 6
      1996319.63       300455.64      1996512.85       300237.43
      1996745.88       299910.39      1996859.57       299771.59
      1996994.95       299651.01      1997035.73        299614.7
#Sta/Elev= 30
       0   55.01  183.26   51.12  228.32   51.34  252.42   49.57  300.77   48.54
   339.1   48.88  398.95   45.72  634.38   44.95  735.52   41.82  797.04   41.58
   808.8   42.63  820.77   41.58  872.41      44  891.59   43.93  899.25    42.1
  903.63   42.87  915.22      42  926.25      44  951.41   42.17  965.04   43.38
     970    38.5     995    38.5   996.6   42.43  998.14   42.75 1009.14   43.56
 1021.34   41.95 1040.91   42.98 1057.46   48.28 1077.85   52.84 1108.34   54.99
#Mann= 3 ,-1,0
       0     .15       0  965.04     .08       0  998.14     .15       0
#XS Ineff= 2 , 0
             605    48.8    1035            48.8
Permanent Ineff=
       F       F
Bank Sta=965.04,998.14
XS Rating Curve= 0 ,0
Exp/Cntr=0.5,0.3

Type RM Length L Ch R = 1 ,13521.47,485,621.98,500
XS GIS Cut Line= 6
       1996830.9        301050.3       1997085.9        300721.2
       1997249.6        300505.3      1997253.11       300500.65
       1997396.3        300311.8       1997537.1        300095.4
#Sta/Elev= 30
       0   55.18   38.11   52.18   57.29    51.6    62.8   52.52   79.71   50.83
  183.19   47.51  226.27   48.05  237.33   47.21  266.86   48.26  327.21   46.22
  395.89   45.32   461.3   45.86   511.4   44.94  545.98    45.7  561.77   44.44
  621.03    43.1  643.52   41.14  661.66   40.73  815.99   40.74  844.61   41.57
 1027.64    40.8    1030   37.87    1055   37.87 1057.84   41.14 1081.35    40.9
 1108.59   43.53 1148.19   48.25 1169.56   51.89 1180.53   52.68 1188.27   54.96
#Mann= 3 ,-1,0
       0     .15       0 1027.64     .08       0 1057.84     .15       0
Bank Sta=1027.64,1057.84
XS Rating Curve= 0 ,0
Exp/Cntr=0.3,0.1

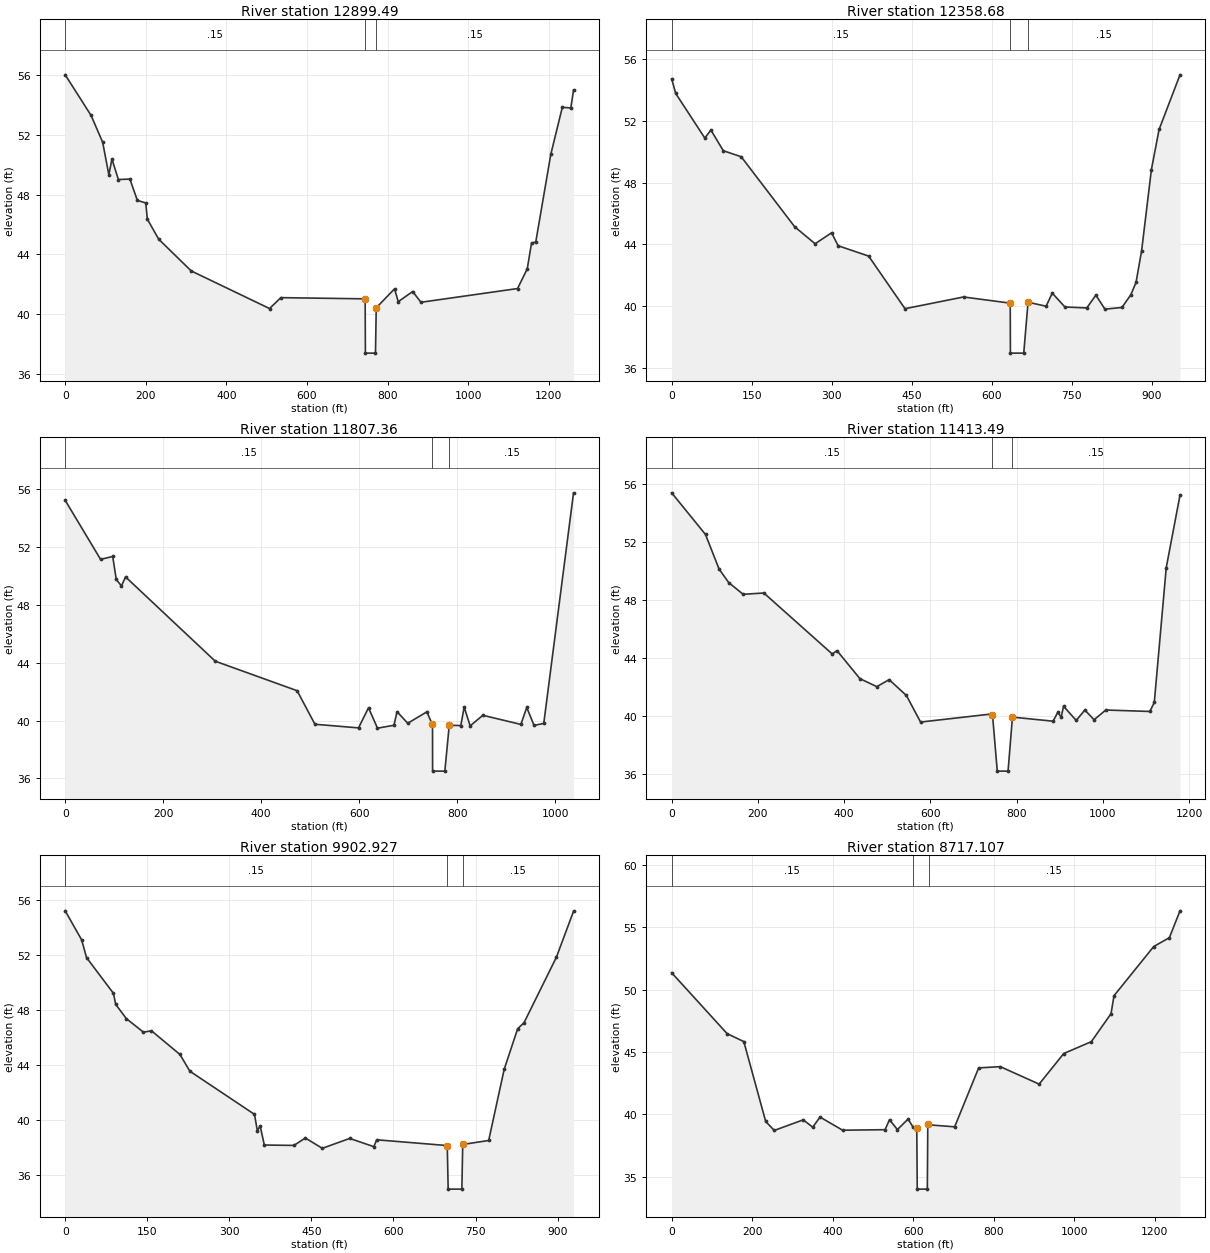
Type RM Length L Ch R = 1 ,12899.49,410,540.81,550
XS GIS Cut Line= 6
       1997073.1        301268.8      1997451.63       300901.83
      1997463.36       300890.44      1997519.47       300836.06
      1997552.45       300804.07      1997978.85       300390.69
#Sta/Elev= 30
       0   56.03   64.14   53.31   92.95   51.51  108.31   49.33     116   50.38
  131.96   49.01  160.51   49.04  179.09   47.61  199.97   47.44  203.73   46.36
  231.96   45.01   312.8   42.88  507.09   40.36  535.13   41.09  744.41   41.01
     745   37.37     770   37.37   771.9   40.41  817.34   41.68  826.54   40.82
  862.23    41.5  882.96   40.78  1122.6    41.7 1146.67   43.02 1157.28   44.75
  1167.8   44.82 1205.12    50.7 1233.67   53.85 1254.74   53.81 1261.53      55
#Mann= 3 ,-1,0
       0     .15       0  744.41     .08       0   771.9     .15       0
Bank Sta=744.41,771.9
XS Rating Curve= 0 ,0
Exp/Cntr=0.3,0.1

Type RM Length L Ch R = 1 ,12358.68,495,551.32,590
XS GIS Cut Line= 6
       1997232.1        301511.1      1997729.16       301258.35
      1997770.86       301237.16      1997793.35       301225.71
       1997802.6       301221.02       1998081.5        301079.2
#Sta/Elev= 30
       0   54.73     7.6   53.78   62.15   50.89   73.52   51.41   96.76   50.07
  130.35   49.68  230.61   45.14  268.89   44.04  299.74   44.75  312.06   43.91
  369.25   43.24  437.39   39.83  547.11   40.59  634.66   40.19     635   36.95
     660   36.95  668.05   40.25  701.89   39.99  713.46   40.84  737.19   39.94
   778.2   39.88  795.21   40.71  812.16    39.8  844.09   39.91  860.67   40.73
  870.48   41.53  880.99    43.6   899.3   48.85  913.72   51.45   952.9   54.99
#Mann= 3 ,-1,0
       0     .15       0  634.66     .08       0  668.05     .15       0
Bank Sta=634.66,668.05
XS Rating Curve= 0 ,0
Exp/Cntr=0.3,0.1

Type RM Length L Ch R = 1 ,11807.36,385,393.87,415
XS GIS Cut Line= 6
       1997316.3        301855.7       1997955.8       301718.15
      1998015.13        301705.4      1998112.53       301684.44
      1998130.76       301680.53       1998330.8        301637.5
#Sta/Elev= 30
       0   55.22   72.19   51.14   96.95   51.34  104.24   49.75  114.82    49.3
   123.1   49.93  306.32    44.1   473.4   42.06  509.81   39.74  598.79   39.49
  619.18   40.88  637.47   39.47  671.07   39.67  677.43   40.61  699.27   39.81
  738.34    40.6  749.33   39.73  749.84   39.75     750    36.5     775    36.5
  783.97   39.67  807.61   39.65  814.44   40.93  826.65   39.63  852.58   40.36
  930.19   39.73  942.22    40.9   957.1   39.66  976.93    39.8  1037.7   55.74
#Mann= 3 ,-1,0
       0     .15       0  749.33     .08       0  783.97     .15       0
Bank Sta=749.33,783.97
XS Rating Curve= 0 ,0
Exp/Cntr=0.3,0.1

Type RM Length L Ch R = 1 ,11413.49,1320,1514,1320
XS GIS Cut Line= 6
       1997354.4        302054.8      1997646.65       302092.22
       1997705.8        302099.8       1998144.7        302075.5
       1998330.8        302074.7        1998529.        302089.4
#Sta/Elev= 30
       0   55.36   78.45   52.49  109.91   50.11  132.21   49.18  165.75   48.37
  213.76   48.46  372.28   44.26  383.32   44.49  436.45   42.56  475.66   42.01
   504.3   42.49   544.3    41.4  577.14   39.57  743.09   40.13   743.9   40.08
     755   36.19     780   36.19   790.2   39.91   884.3   39.63   895.2   40.23
  903.18   39.92  908.74   40.66     938   39.68  958.06    40.4  979.41   39.73
 1006.75    40.4  1108.8    40.3 1119.07   40.92 1146.81   50.21 1178.69    55.2
#Mann= 3 ,-1,0
       0     .15       0  743.09     .08       0   790.2     .15       0
Bank Sta=743.9,790.2
XS Rating Curve= 0 ,0
Exp/Cntr=0.3,0.1

Type RM Length L Ch R = 1 ,9902.927,1020,1185.82,1065
XS GIS Cut Line= 6
       1997514.1        303351.1      1997844.77       303401.28
      1997860.38       303403.65      1997861.31        303403.8
       1997865.3        303404.4       1998439.2        303403.5
#Sta/Elev= 30
       0   55.22   30.12    53.1   38.95   51.82   88.11   49.22   92.36   48.41
  111.68   47.38  142.93   46.39  157.69   46.49   209.7   44.77  227.86   43.55
  345.97   40.41  351.19   39.22  356.34   39.57  363.92   38.18  418.05   38.15
  438.92   38.69  469.95   37.94  520.03   38.66  564.08   38.06  569.41   38.56
  698.29   38.14     700   34.97     725   34.97  726.58   38.22  774.03   38.51
  802.38   43.69  826.99   46.64  838.63   47.08  897.76   51.84  929.12   55.19
#Mann= 3 ,-1,0
       0     .15       0  698.29     .08       0  726.58     .15       0
Bank Sta=698.29,726.58
XS Rating Curve= 0 ,0
Exp/Cntr=0.3,0.1

Type RM Length L Ch R = 1 ,8717.107,690,830.98,710
XS GIS Cut Line= 6
       1997218.8        304435.3       1997436.9        304395.4
       1997971.4        304401.2       1998191.4        304429.4
      1998252.29       304518.04       1998355.9        304668.9
#Sta/Elev= 30
       0   51.35   137.8   46.47  179.15   45.84  233.52   39.44  254.81   38.72
  326.83   39.57   350.3   38.98  368.51   39.79   424.5   38.74  530.03   38.78
  541.05   39.58  560.67   38.79  587.21   39.63  599.13   39.01  608.78    38.9
     610   34.02     635   34.02  636.14   39.22  638.49   39.17  702.87   39.01
  762.51   43.73  816.14   43.83  912.76   42.43  973.79   44.88 1042.36   45.83
 1091.29   48.07 1098.65   49.51 1197.31   53.45 1236.24   54.16 1262.59   56.31
#Mann= 3 ,-1,0
       0     .15       0  599.13     .08       0  638.49     .15       0
Bank Sta=608.78,636.14
XS Rating Curve= 0 ,0
Exp/Cntr=0.3,0.1

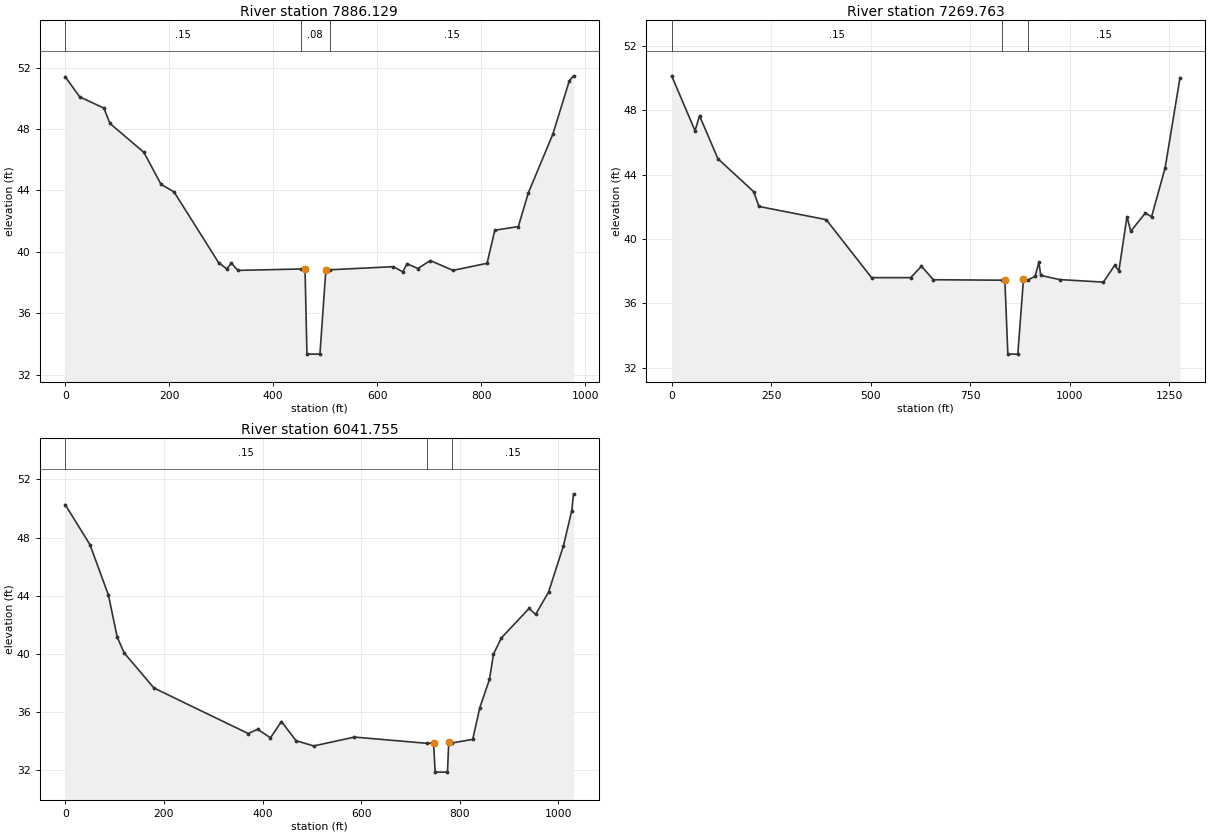
Type RM Length L Ch R = 1 ,7886.129,625,616.37,530
XS GIS Cut Line= 6
       1997060.1        305042.8      1997076.98       305044.17
      1997213.65       305055.21      1997246.06       305057.84
      1997325.33       305064.24       1998034.7        305121.6
#Sta/Elev= 30
       0    51.4   27.95   50.09    74.4   49.36   86.14   48.36  151.36   46.48
  184.29    44.4  209.29   43.91  294.92   39.31  310.46    38.9  319.72   39.27
  332.13    38.8  453.06   38.89   461.3   38.87     465   33.35     490   33.35
  501.29    38.8  509.05   38.84  631.03   39.04  649.31   38.71  657.66   39.23
  678.39   38.92  702.26   39.44  745.87    38.8  811.44   39.26  826.34   41.41
  871.61   41.65  890.81   43.84  937.82   47.65  969.71   51.14  977.78   51.46
#Mann= 3 ,-1,0
       0     .15       0  453.06     .08       0  509.05     .15       0
Bank Sta=461.3,501.29
XS Rating Curve= 0 ,0
Exp/Cntr=0.3,0.1

Type RM Length L Ch R = 1 ,7269.763,204.18,245.51,213.04
XS GIS Cut Line= 6
       1997055.4        306149.5      1997215.57       306031.39
      1997227.28       306022.74       1997227.6       306022.52
       1997740.2        305644.5        1998124.        305457.7
#Sta/Elev= 30
       0   50.13   58.71   46.72   70.01   47.65  116.29   44.98  206.03   42.94
  219.28   42.02  388.44    41.2  502.39    37.6  600.81    37.6  627.82   38.31
  657.71   37.47  831.19   37.44   837.5   37.44     845   32.85     870   32.85
  884.27    37.5  895.21   37.45  913.38   37.68  923.07   38.55  927.66   37.74
  974.91   37.48  1085.2   37.32 1113.34   38.36 1124.13   38.03 1144.44   41.38
 1154.04   40.48 1190.54   41.61 1206.27   41.38 1240.38   44.42 1277.71   50.02
#Mann= 3 ,-1,0
       0     .15       0  831.19     .08       0  895.21     .15       0
Bank Sta=837.5,884.27
XS Rating Curve= 0 ,0
Exp/Cntr=0.3,0.1

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
Type RM Length L Ch R = 1 ,6041.755,0,0,0
XS GIS Cut Line= 6
       1997539.5        306890.7      1998138.86       306579.35
      1998225.69       306534.23      1998253.07       306520.02
        1998312.        306489.4        1998465.        306442.6
#Sta/Elev= 30
       0   50.27   50.16   47.52    87.6   44.05  105.45   41.16  119.46   40.08
  179.98   37.66  371.18   34.53  390.04   34.83  416.13   34.24  438.29   35.36
  467.99   34.04  503.92   33.68  586.36   34.29  733.51   33.86   746.8   33.88
     750   31.88     775   31.88   777.5   33.92  784.75   33.89  826.09   34.13
  840.58   36.32  860.12   38.25  868.18   39.99   884.3   41.11   940.3   43.13
  953.64   42.72  979.81   44.25 1010.14   47.45 1026.87   49.85 1030.51   51.01
#Mann= 3 ,-1,0
       0     .15       0  733.51     .08       0  784.75     .15       0
Bank Sta=746.8,777.5
XS Rating Curve= 0 ,0
Exp/Cntr=0.3,0.1
LCMann Table=0

Chan Stop Cuts=-1
Use User Specified Reach Order=0
Composite Channel Slope=5

--- US278overBeaver.g01 (geometry) ---

Geom Title=Natural Geometry
Program Version=6.50

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
River Reach=Beaver Dam Creek,Reach 1

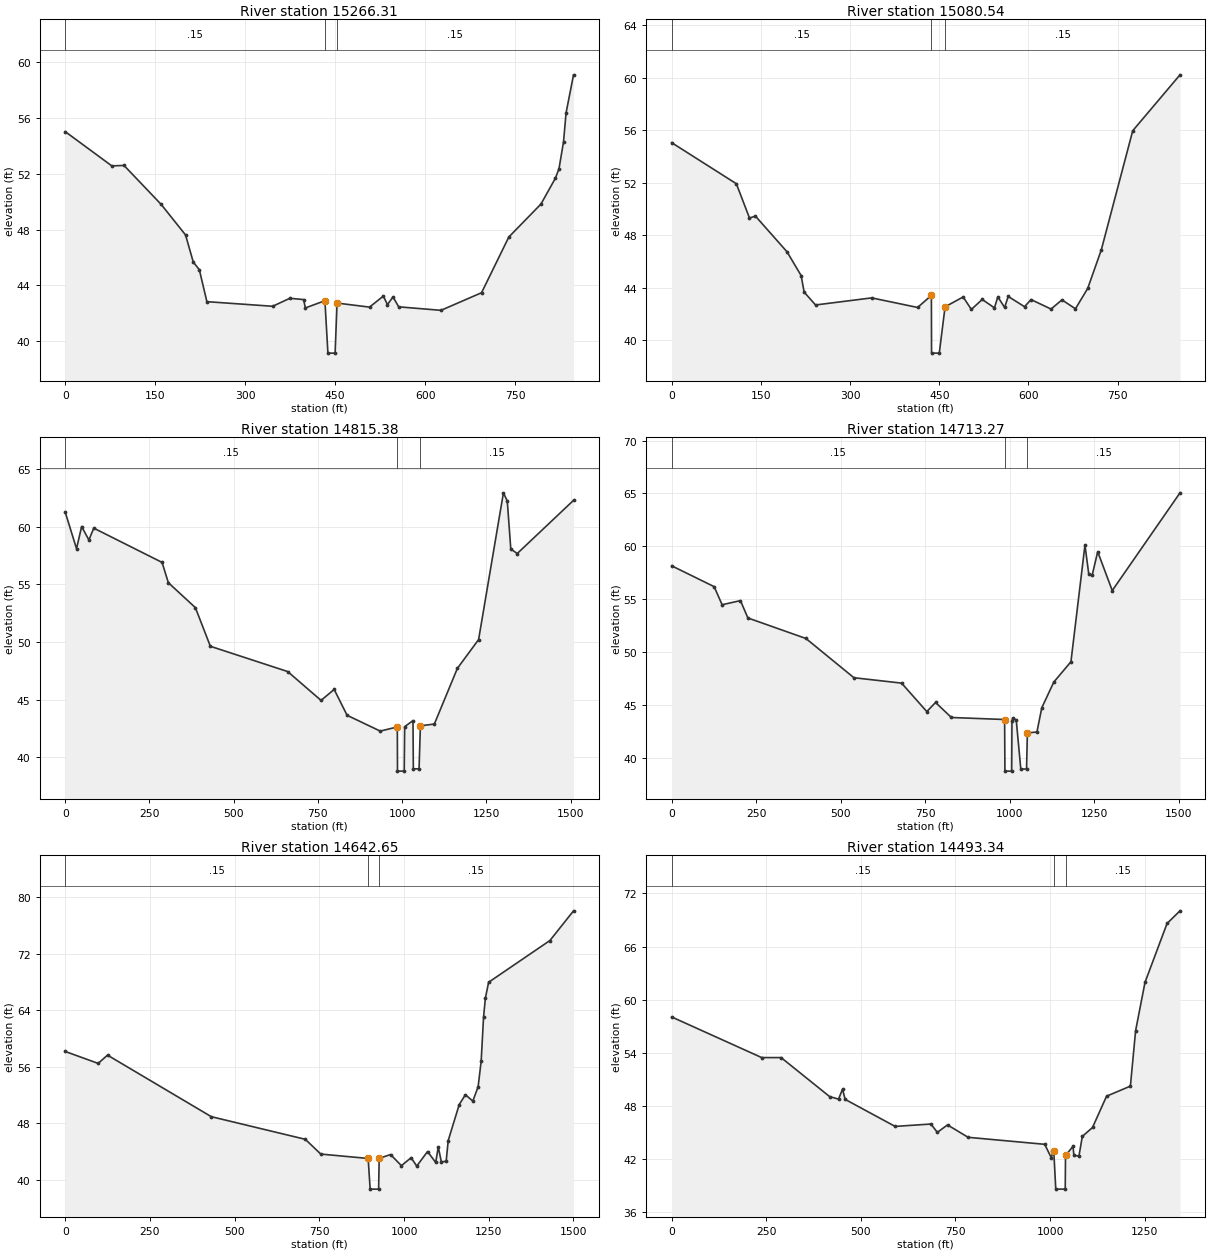
Type RM Length L Ch R = 1 ,15266.31,185,185.78,160
XS GIS Cut Line= 6
      1995802.76       299546.81      1995818.88       299536.57
      1995819.54       299536.14      1995850.85       299516.26
       1996190.1        299300.7       1996508.8        299078.4
#Sta/Elev= 30
       0      55   77.67   52.55   98.05   52.58  159.88    49.8  200.65   47.61
  213.51   45.67  223.67   45.12   236.2   42.84  345.87   42.51  374.48   43.08
  397.45   42.99  400.41   42.39  432.98   42.91     438   39.16     450   39.16
  453.22   42.74  507.33   42.45  530.48   43.24  537.18   42.63  546.56   43.18
  555.96   42.47  626.49   42.22  694.16   43.48  739.58   47.46  793.18   49.82
  817.15   51.66  823.23   52.34  830.78   54.26  835.06   56.34  847.49   59.06
#Mann= 3 ,-1,0
       0     .15       0  432.98     .08       0  453.22     .15       0
Bank Sta=432.98,453.22
XS Rating Curve= 0 ,0
Exp/Cntr=0.3,0.1

Type RM Length L Ch R = 1 ,15080.54,300,265.15,200
XS GIS Cut Line= 6
       1995928.8        299751.4      1996262.01       299467.02
       1996349.5       299392.37      1996380.11       299366.23
      1996397.66       299351.27        1996579.        299196.5
#Sta/Elev= 30
       0   55.05  108.76   51.92  130.83   49.31  140.91   49.45  194.01   46.73
  217.69   44.92  222.76   43.66  241.94   42.68  336.42   43.22  413.55   42.49
  436.75   43.41     437   39.01     450   39.01  459.73   42.54  490.17   43.29
   503.9   42.34  522.22    43.1  542.77   42.46  548.45    43.3  559.89   42.49
  565.94   43.33  593.33   42.55  604.34   43.09  637.94   42.37  656.26   43.07
  678.98   42.39  699.58   43.94  722.46   46.88  775.31   55.96  854.79   60.22
#Mann= 3 ,-1,0
       0     .15       0  436.75     .08       0  459.73     .15       0
Bank Sta=436.75,459.73
XS Rating Curve= 0 ,0
Exp/Cntr=0.3,0.1

Type RM Length L Ch R = 1 ,14815.38,100,102.11,100
XS GIS Cut Line= 6
       1996029.1        300452.3       1996418.2        299711.1
       1996585.8        299387.3      1996615.49       299336.45
      1996628.47       299314.25       1996740.8        299121.9
#Sta/Elev= 30
       0   61.25   33.61   58.08   48.76      60   70.29   58.83   84.72   59.86
  287.42   56.89  306.07   55.13  386.26   52.97  430.73   49.62  660.18   47.43
  759.16   44.93  798.09   45.88  836.43   43.64  934.77   42.27  985.49   42.63
     986    38.8    1006    38.8 1007.28   42.65 1032.02   43.18    1033      39
    1050      39 1053.97   42.73 1095.35   42.88 1163.77   47.71 1226.66    50.2
 1300.36   62.92 1311.77   62.21 1322.22   58.05 1341.36   57.66 1508.37   62.27
#Mann= 3 ,-1,0
       0     .15       0  985.49     .08       0 1053.97     .15       0
Bank Sta=985.49,1053.97
XS Rating Curve= 0 ,0
Exp/Cntr=0.3,0.1

Type RM Length L Ch R = 1 ,14713.27,70,70.62,80
XS GIS Cut Line= 6
       1996117.9        300498.9       1996334.9        300080.2
       1996482.6        299802.5      1996575.68       299626.62
       1996672.1        299444.4       1996826.3        299172.3
#Sta/Elev= 30
       0   58.16  125.69   56.19  149.21   54.48  203.48   54.87  225.54   53.23
  397.23   51.29  539.23   47.58  680.28   47.07  754.84   44.38  780.77   45.24
  827.69   43.82  985.12   43.63     986   38.75    1006   38.75 1006.88   43.49
 1009.07   43.76 1019.51   43.58    1033   38.95    1050   38.95 1052.46   42.36
 1080.72   42.45 1095.14   44.74 1130.66   47.17 1181.34   49.09 1222.82   60.12
 1234.19   57.36 1244.15   57.27 1260.57   59.49 1303.56   55.82 1504.03   65.06
#Mann= 3 ,-1,0
       0     .15       0  985.12     .08       0 1052.46     .15       0
Bank Sta=985.12,1052.46
XS Rating Curve= 0 ,0
Exp/Cntr=0.3,0.1

Type RM Length L Ch R = 1 ,14642.65,75,100,80
XS GIS Cut Line= 6
       1996144.3        300506.6       1996178.5        300455.9
        1996520.        299864.2       1996797.7        299378.3
      1996798.91       299376.09       1996892.4        299206.4
#Sta/Elev= 30
       0   58.17   97.19   56.48  124.85   57.65  431.24   48.94   708.6   45.74
  754.25   43.65  894.11   43.03     900   38.69     925   38.69  926.61   43.05
  960.26   43.58   992.3   42.01 1020.97   43.14  1037.4   41.95 1069.45   44.01
  1093.5   42.46 1101.03   44.65 1110.09   42.56 1124.35   42.62 1130.35   45.56
 1162.88   50.65  1181.1   52.05 1203.06   51.15 1218.72   53.19 1227.64   56.79
 1234.65      63 1240.05    65.7 1249.62   67.96 1430.59   73.87 1500.25   78.07
#Mann= 3 ,-1,0
       0     .15       0  894.11     .08       0  926.61     .15       0
Bank Sta=894.11,926.61
XS Rating Curve= 0 ,0
Exp/Cntr=0.3,0.1

Type RM Length L Ch R = 1 ,14493.34,165,150,200
XS GIS Cut Line= 6
       1996175.6         300528.       1996340.1        300284.1
        1996567.        299861.2      1996729.96       299689.61
       1996744.7        299674.1       1996822.2        299372.8
#Sta/Elev= 30
       0   58.05  237.96   53.46  289.24   53.46  417.35   49.06  440.92   48.77
  451.47   49.89  458.48   48.74  590.54   45.69  684.92   45.96   702.1   45.02
  728.91   45.86  783.38   44.46  985.74   43.67 1002.81   42.18 1009.67   42.93
    1015   38.61    1040   38.61 1040.73   42.41 1041.18   42.42  1060.5   43.44
 1062.86   42.43 1076.23   42.34 1085.14   44.56 1112.13   45.57 1149.19    49.1
 1212.16   50.24 1225.98    56.5 1250.83   61.96 1309.03    68.6 1343.26   70.03
#Mann= 3 ,-1,0
       0     .15       0 1009.67     .08       0 1041.18     .15       0
Bank Sta=1009.67,1041.18
XS Rating Curve= 0 ,0
Exp/Cntr=0.3,0.1