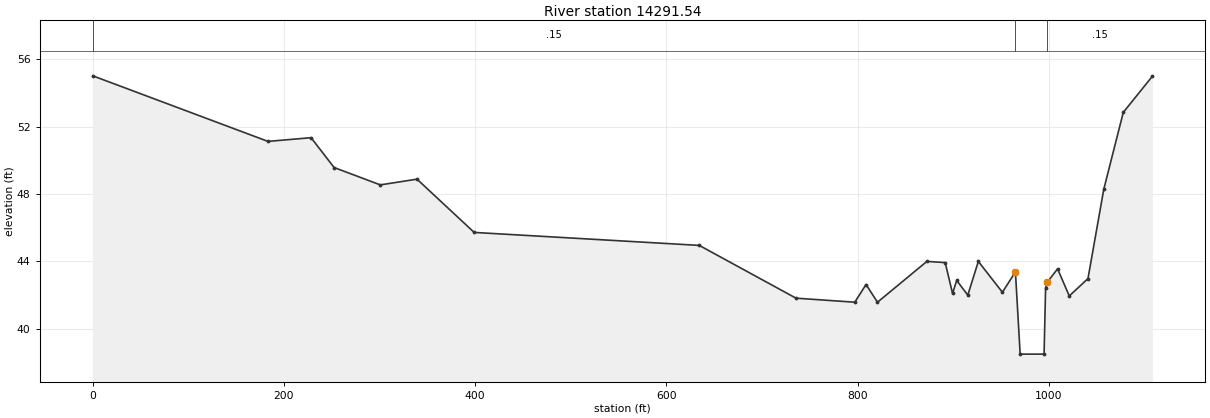
HEC-RAS study US278overBeaver.prj: US 278 over Beaver Dam Cr_Prelim

--- US278overBeaver.g01 (geometry) --- (continued)

Type RM Length L Ch R = 1 ,14291.54,775,770.07,725
XS GIS Cut Line= 6
      1996319.63       300455.64      1996512.85       300237.43
      1996745.88       299910.39      1996859.57       299771.59
      1996994.95       299651.01      1997035.73        299614.7
#Sta/Elev= 30
       0   55.01  183.26   51.12  228.32   51.34  252.42   49.57  300.77   48.54
   339.1   48.88  398.95   45.72  634.38   44.95  735.52   41.82  797.04   41.58
   808.8   42.63  820.77   41.58  872.41      44  891.59   43.93  899.25    42.1
  903.63   42.87  915.22      42  926.25      44  951.41   42.17  965.04   43.38
     970    38.5     995    38.5   996.6   42.43  998.14   42.75 1009.14   43.56
 1021.34   41.95 1040.91   42.98 1057.46   48.28 1077.85   52.84 1108.34   54.99
#Mann= 3 ,-1,0
       0     .15       0  965.04     .08       0  998.14     .15       0
Bank Sta=965.04,998.14
XS Rating Curve= 0 ,0
Exp/Cntr=0.3,0.1

--- US278overBeaver.g02 (geometry) ---

Geom Title=Natural Geometry_Rough2
Program Version=6.50

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
River Reach=Beaver Dam Creek,Reach 1

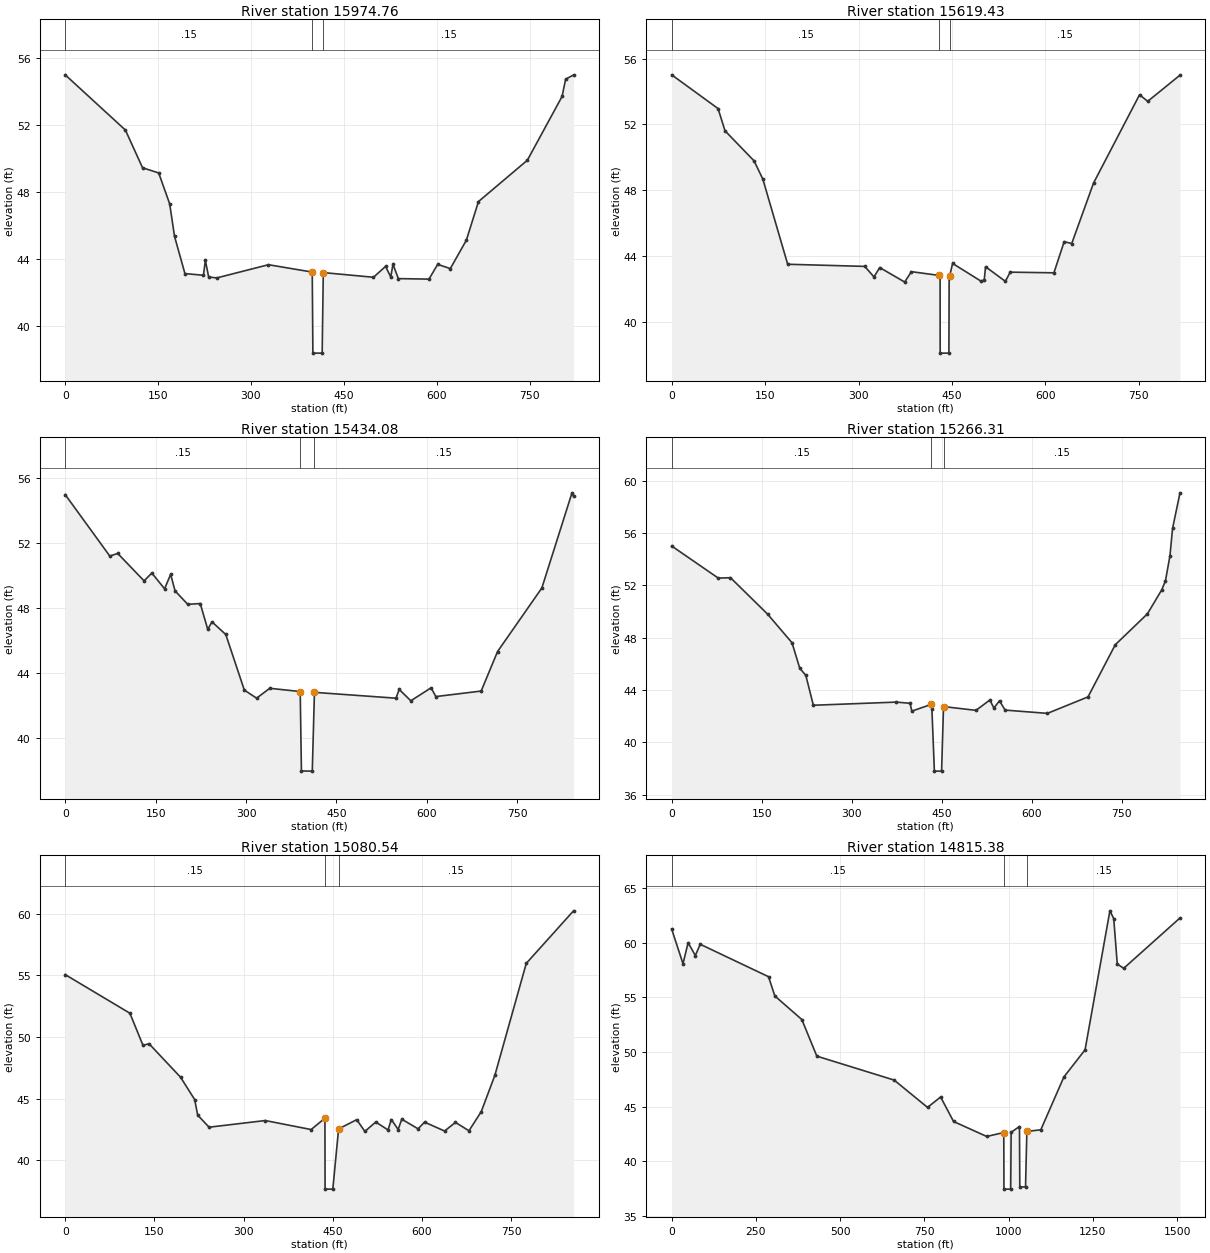
Type RM Length L Ch R = 1 ,15974.76,370,355.33,340
XS GIS Cut Line= 6
      1995520.95       298763.35      1996209.87       298577.81
      1996216.18        298576.1      1996218.86       298575.39
      1996261.44       298563.91      1996313.63       298549.86
#Sta/Elev= 30
       0      55   97.23    51.7  124.91   49.45  150.98   49.14  168.76   47.29
  176.51   45.36  193.36   43.13  223.26   43.03  226.34   43.92  231.67   42.93
  244.61   42.87  328.28   43.66  398.96   43.22     400   38.38     415   38.38
  416.78   43.19  497.83   42.91  517.37   43.56  525.73   42.93  529.36   43.68
  538.04   42.83  587.45    42.8  601.54   43.68  621.96   43.43   647.8   45.12
  667.39   47.43  746.36    49.9  802.44   53.71  808.16   54.74  820.93   54.99
#Mann= 3 ,-1,0
       0     .15       0  398.96     .08       0  416.78     .15       0
Bank Sta=398.96,416.78
XS Rating Curve= 0 ,0
Exp/Cntr=0.3,0.1

Type RM Length L Ch R = 1 ,15619.43,210,185.35,150
XS GIS Cut Line= 6
      1995645.63       299159.32      1996043.66       298984.54
      1996048.88       298982.26      1996058.53       298978.01
      1996105.04        298957.6      1996392.75       298831.26
#Sta/Elev= 30
       0   55.01   74.47   52.96   85.61   51.61  132.31   49.78  146.37   48.67
  186.22    43.5  309.91   43.37  324.79   42.73  333.94    43.3  373.99   42.42
  384.84   43.05  429.61   42.82  430.88   42.74     431    38.1     445    38.1
   445.4   42.64  446.07   42.76  450.96   43.55  496.68   42.47  501.74   42.55
  503.85   43.35  535.66   42.46  543.39   43.02  613.59   42.98  630.03   44.87
  642.18   44.76  677.26   48.44  751.06    53.8  764.13    53.4  815.97   54.99
#Mann= 3 ,-1,0
       0     .15       0  429.61     .08       0  446.07     .15       0
Bank Sta=429.61,446.07
XS Rating Curve= 0 ,0
Exp/Cntr=0.3,0.1

Type RM Length L Ch R = 1 ,15434.08,145,167.76,160
XS GIS Cut Line= 6
       1995723.1       299437.56      1996074.88       299187.75
      1996275.53       299017.88      1996279.15        299014.8
      1996346.01       298958.21      1996389.38       298921.48
#Sta/Elev= 30
       0      55   73.97   51.21   87.17   51.37  130.85   49.68  143.76   50.16
   164.9   49.19  174.98   50.08  182.31   49.06  203.35   48.23  224.11   48.28
  236.51   46.69  243.54   47.15  266.46   46.37  297.25   42.94  317.62   42.44
  339.45   43.05  389.98   42.85     392   37.95     410   37.94  413.59    42.8
  548.87   42.44  554.23   42.98  573.54   42.28  607.14   43.08  615.08   42.54
  690.26   42.88   717.5   45.32  790.97   49.24  840.99   55.11  843.54   54.89
#Mann= 3 ,-1,0
       0     .15       0  389.98     .08       0  413.59     .15       0
Bank Sta=389.98,413.59
XS Rating Curve= 0 ,0
Exp/Cntr=0.3,0.1

Type RM Length L Ch R = 1 ,15266.31,185,185.78,160
XS GIS Cut Line= 6
      1995802.76       299546.81      1995818.88       299536.57
      1995819.54       299536.14      1995850.85       299516.26
       1996190.1        299300.7       1996508.8        299078.4
#Sta/Elev= 30
       0      55   77.67   52.55   98.05   52.58  159.88    49.8  200.65   47.61
  213.51   45.67  223.67   45.12   236.2   42.84  374.48   43.08  397.45   42.99
  400.41   42.39  432.98   42.91  433.84   42.57     438   37.81     450   37.81
  453.22   42.74  507.33   42.45  530.48   43.24  537.18   42.63  546.56   43.18
  555.96   42.47  626.49   42.22  694.16   43.48  739.58   47.46  793.18   49.82
  817.15   51.66  823.23   52.34  830.78   54.26  835.06   56.34  847.49   59.06
#Mann= 3 ,-1,0
       0     .15       0  432.98     .08       0  453.22     .15       0
Bank Sta=432.98,453.22
XS Rating Curve= 0 ,0
Exp/Cntr=0.3,0.1

Type RM Length L Ch R = 1 ,15080.54,300,265.15,200
XS GIS Cut Line= 6
       1995928.8        299751.4      1996262.01       299467.02
       1996349.5       299392.37      1996380.11       299366.23
      1996397.66       299351.27        1996579.        299196.5
#Sta/Elev= 30
       0   55.05  108.76   51.92  130.83   49.31  140.91   49.45  194.01   46.73
  217.69   44.92  222.76   43.66  241.94   42.68  336.42   43.22  413.55   42.49
  436.75   43.41     437   37.66     450   37.66  459.73   42.54  490.17   43.29
   503.9   42.34  522.22    43.1  542.77   42.46  548.45    43.3  559.89   42.49
  565.94   43.33  593.33   42.55  604.34   43.09  637.94   42.37  656.26   43.07
  678.98   42.39  699.58   43.94  722.46   46.88  775.31   55.96  854.79   60.22
#Mann= 3 ,-1,0
       0     .15       0  436.75     .08       0  459.73     .15       0
Bank Sta=436.75,459.73
XS Rating Curve= 0 ,0
Exp/Cntr=0.3,0.1

Type RM Length L Ch R = 1 ,14815.38,50,51.67,50
XS GIS Cut Line= 6
       1996029.1        300452.3       1996418.2        299711.1
       1996585.8        299387.3      1996615.49       299336.45
      1996628.47       299314.25       1996740.8        299121.9
#Sta/Elev= 30
       0   61.25   33.61   58.08   48.76      60   70.29   58.83   84.72   59.86
  287.42   56.89  306.07   55.13  386.26   52.97  430.73   49.62  660.18   47.43
  759.16   44.93  798.09   45.88  836.43   43.64  934.77   42.27  985.49   42.63
     986   37.45    1006   37.45 1007.28   42.65 1032.02   43.18    1033   37.65
    1050   37.65 1053.97   42.73 1095.35   42.88 1163.77   47.71 1226.66    50.2
 1300.36   62.92 1311.77   62.21 1322.22   58.05 1341.36   57.66 1508.37   62.27
#Mann= 3 ,-1,0
       0     .15       0  985.49     .08       0 1053.97     .15       0
Bank Sta=985.49,1053.97
XS Rating Curve= 0 ,0
Exp/Cntr=0.3,0.1

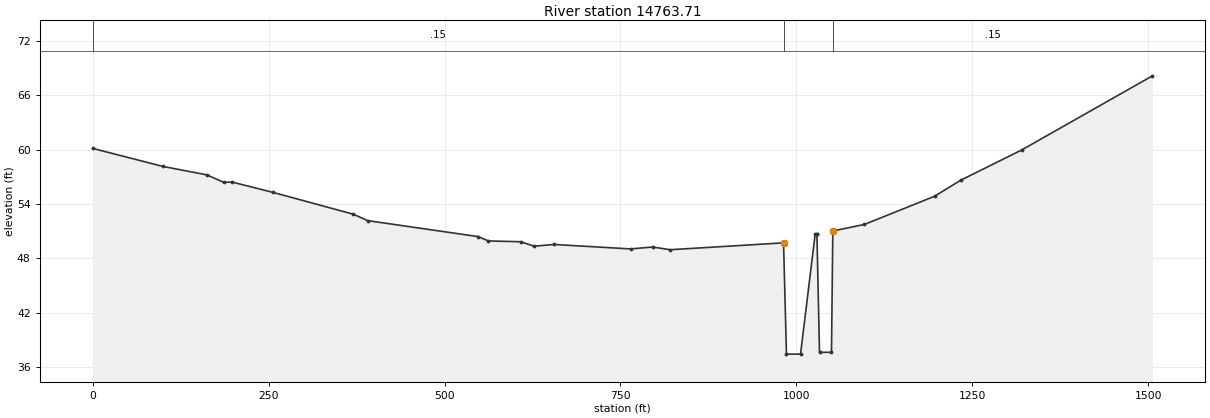
Type RM Length L Ch R = 1 ,14763.71,50,50.44,50
BEGIN DESCRIPTION:
US 278 CENTERLINE STATION
END DESCRIPTION:
XS GIS Cut Line= 6
       1996072.8         300473.      1996444.67       299767.85
      1996444.85       299767.53       1996463.9        299731.4
       1996647.8        299380.5       1996784.5        299145.8
#Sta/Elev= 30
       0   60.12   99.81   58.13  162.22    57.2  186.05   56.38  197.95   56.41
  255.53   55.28  369.93   52.87  390.87   52.15  547.58   50.39  562.45   49.91
  608.26   49.82  627.37   49.33  655.63   49.52  764.32   49.03  795.89   49.24
  820.64   48.94  981.87    49.7     986   37.42    1006   37.42 1026.77   50.63
 1029.02   50.69 1029.28   50.67    1033   37.62    1050   37.62 1051.89   51.01
 1096.75   51.73 1196.52   54.84 1233.91   56.62 1320.17   59.94 1506.19   68.13
#Mann= 3 ,-1,0
       0     .15       0  981.87     .08       0 1051.89     .15       0
Bank Sta=981.87,1051.89
XS Rating Curve= 0 ,0
Exp/Cntr=0.3,0.1