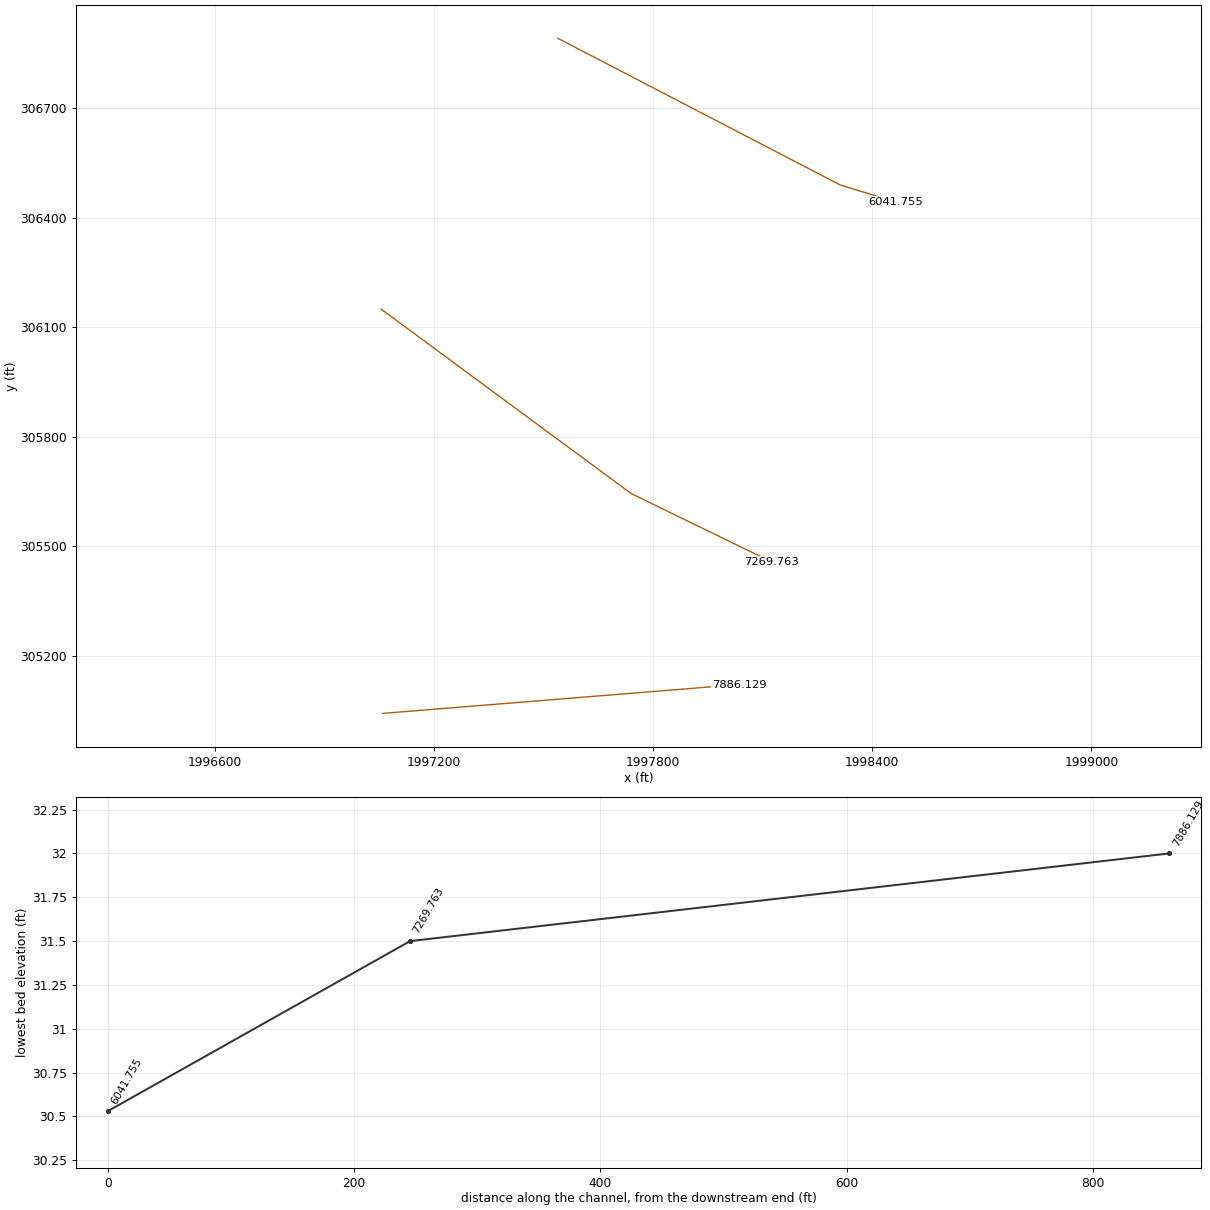
HEC-RAS study US278overBeaver.prj: US 278 over Beaver Dam Cr_Prelim

--- US278overBeaver.g04 (geometry) --- (continued)

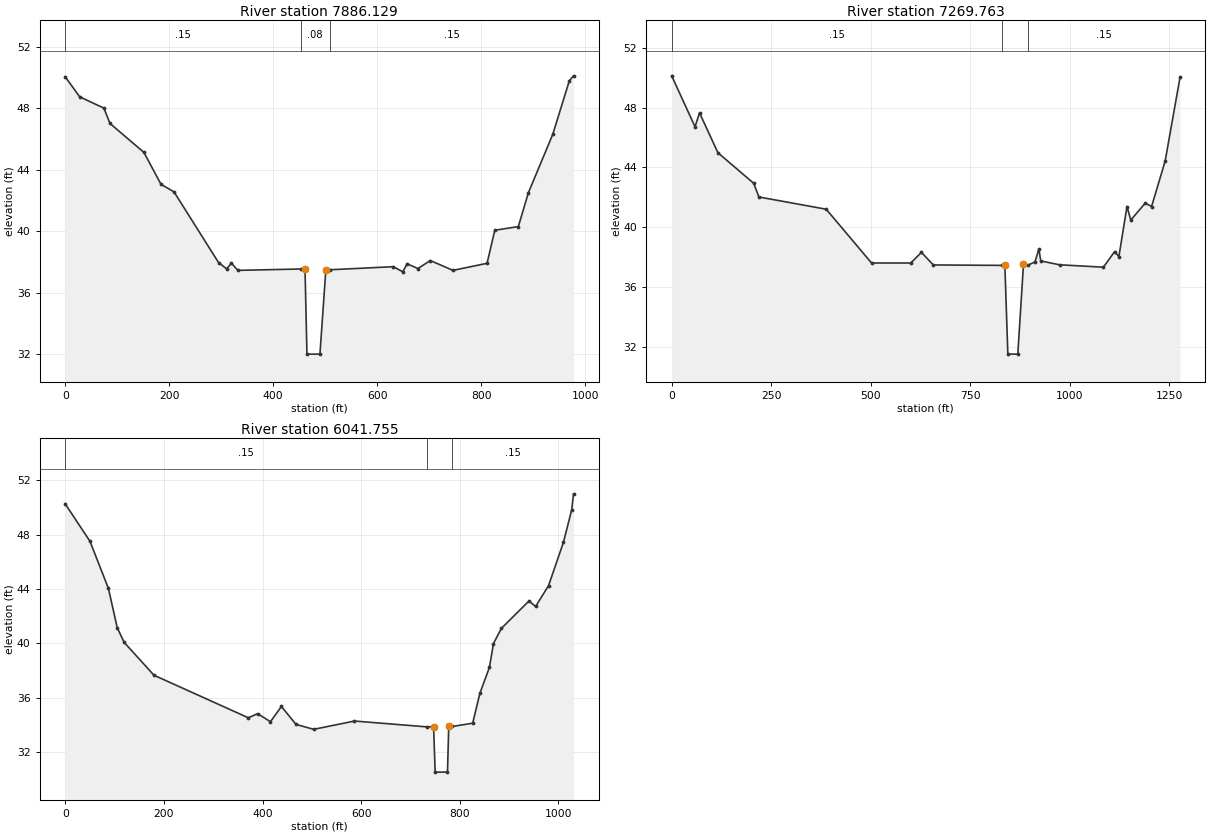
Type RM Length L Ch R = 1 ,7886.129,625,616.37,530
XS GIS Cut Line= 6
       1997060.1        305042.8      1997076.98       305044.17
      1997213.65       305055.21      1997246.06       305057.84
      1997325.33       305064.24       1998034.7        305121.6
#Sta/Elev= 30
       0   50.05   27.95   48.74    74.4   48.01   86.14   47.01  151.36   45.13
  184.29   43.05  209.29   42.56  294.92   37.96  310.46   37.55  319.72   37.92
  332.13   37.45  453.06   37.54   461.3   37.52     465      32     490      32
  501.29   37.45  509.05   37.49  631.03   37.69  649.31   37.36  657.66   37.88
  678.39   37.57  702.26   38.09  745.87   37.45  811.44   37.91  826.34   40.06
  871.61    40.3  890.81   42.49  937.82    46.3  969.71   49.79  977.78   50.11
#Mann= 3 ,-1,0
       0     .15       0  453.06     .08       0  509.05     .15       0
Bank Sta=461.3,501.29
XS Rating Curve= 0 ,0
Exp/Cntr=0.3,0.1

Type RM Length L Ch R = 1 ,7269.763,204.18,245.51,213.04
XS GIS Cut Line= 6
       1997055.4        306149.5      1997215.57       306031.39
      1997227.28       306022.74       1997227.6       306022.52
       1997740.2        305644.5        1998124.        305457.7
#Sta/Elev= 30
       0   50.13   58.71   46.72   70.01   47.65  116.29   44.98  206.03   42.94
  219.28   42.02  388.44    41.2  502.39    37.6  600.81    37.6  627.82   38.31
  657.71   37.47  831.19   37.44   837.5   37.44     845    31.5     870    31.5
  884.27    37.5  895.21   37.45  913.38   37.68  923.07   38.55  927.66   37.74
  974.91   37.48  1085.2   37.32 1113.34   38.36 1124.13   38.03 1144.44   41.38
 1154.04   40.48 1190.54   41.61 1206.27   41.38 1240.38   44.42 1277.71   50.02
#Mann= 3 ,-1,0
       0     .15       0  831.19     .08       0  895.21     .15       0
Bank Sta=837.5,884.27
XS Rating Curve= 0 ,0
Exp/Cntr=0.3,0.1

Type RM Length L Ch R = 1 ,6041.755,0,0,0
XS GIS Cut Line= 6
       1997539.5        306890.7      1998138.86       306579.35
      1998225.69       306534.23      1998253.07       306520.02
        1998312.        306489.4        1998465.        306442.6
#Sta/Elev= 30
       0   50.27   50.16   47.52    87.6   44.05  105.45   41.16  119.46   40.08
  179.98   37.66  371.18   34.53  390.04   34.83  416.13   34.24  438.29   35.36
  467.99   34.04  503.92   33.68  586.36   34.29  733.51   33.86   746.8   33.88
     750   30.53     775   30.53   777.5   33.92  784.75   33.89  826.09   34.13
  840.58   36.32  860.12   38.25  868.18   39.99   884.3   41.11   940.3   43.13
  953.64   42.72  979.81   44.25 1010.14   47.45 1026.87   49.85 1030.51   51.01
#Mann= 3 ,-1,0
       0     .15       0  733.51     .08       0  784.75     .15       0
Bank Sta=746.8,777.5
XS Rating Curve= 0 ,0
Exp/Cntr=0.3,0.1
LCMann Table=0

--- US278overBeaver.g05 (geometry) ---

Geom Title=Prop Cond_Culverts_2-Double 10x10
Program Version=6.50

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
River Reach=Beaver Dam Creek,Reach 1

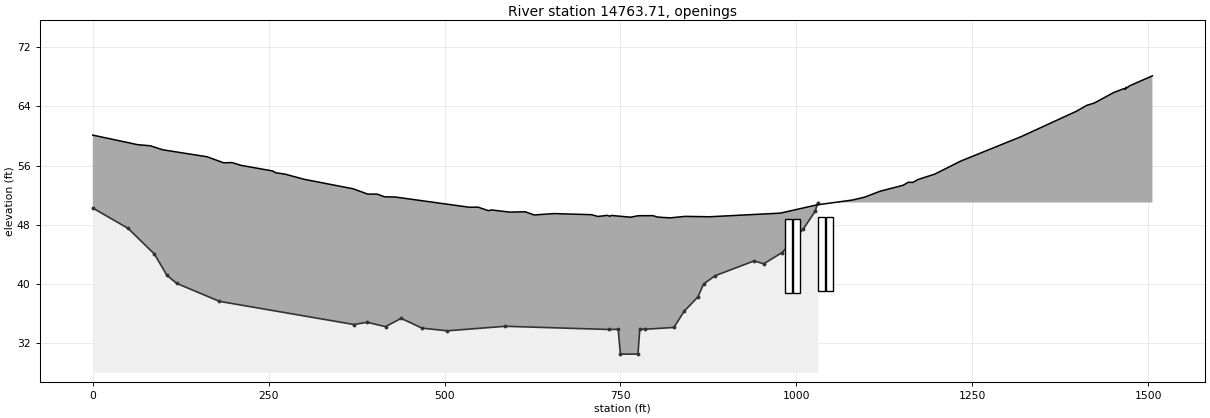
Type RM Length L Ch R = 4 ,14763.71,,,
Bridge Culvert--1,0,-1,-1, 0
Deck Dist Width WeirC Skew NumUp NumDn MinLoCord MaxHiCord MaxSubmerge Is_Ogee
32,30,2.6,0, 60, 60, , , 0.98, 0, 0,0,,
       0   63.78    81.7   99.81  162.22  186.05  197.95  210.94  255.53  260.33
  272.37  300.48  369.93  390.87  404.19  414.57  429.67   535.5  547.58  562.45
  566.78  592.29  614.78  627.37  655.63  708.77  718.15  731.21  735.25  736.79
  764.32  775.26  795.89  803.45  820.64  841.84  876.75  977.36 1029.02 1079.76
 1096.75 1119.48 1151.72  1159.2 1165.72 1172.95 1196.52 1233.91 1320.17 1398.01
 1412.77 1423.47 1451.06 1465.93 1467.23 1468.18 1468.69 1469.53 1473.91 1506.19
   60.12   58.83   58.68   58.13    57.2   56.38   56.41   56.03   55.28   55.02
   54.87   54.15   52.87   52.15   52.15   51.79   51.76   50.37   50.39   49.91
   50.01   49.72   49.76   49.33   49.52   49.37   49.13   49.28   49.15   49.27
   49.03   49.23   49.24   49.04   48.94   49.14   49.09   49.58   50.69   51.35
   51.73   52.55   53.34   53.75   53.73   54.12   54.84   56.62   59.94   63.34
   64.14   64.45   65.87   66.41    66.3   66.35   66.59   66.49   66.79   68.13
                                                                                
                                                                                
                                                                                
                                                                                
                                                                                
                                                                                
       0   63.78    81.7   99.81  162.22  186.05  197.95  210.94  255.53  260.33
  272.37  300.48  369.93  390.87  404.19  414.57  429.67   535.5  547.58  562.45
  566.78  592.29  614.78  627.37  655.63  708.77  718.15  731.21  735.25  736.79
  764.32  775.26  795.89  803.45  820.64  841.84  876.75  977.36 1029.02 1079.76
 1096.75 1119.48 1151.72  1159.2 1165.72 1172.95 1196.52 1233.91 1320.17 1398.01
 1412.77 1423.47 1451.06 1465.93 1467.23 1468.18 1468.69 1469.53 1473.91 1506.19
   60.12   58.83   58.68   58.13    57.2   56.38   56.41   56.03   55.28   55.02
   54.87   54.15   52.87   52.15   52.15   51.79   51.76   50.37   50.39   49.91
   50.01   49.72   49.76   49.33   49.52   49.37   49.13   49.28   49.15   49.27
   49.03   49.23   49.24   49.04   48.94   49.14   49.09   49.58   50.69   51.35
   51.73   52.55   53.34   53.75   53.73   54.12   54.84   56.62   59.94   63.34
   64.14   64.45   65.87   66.41    66.3   66.35   66.59   66.49   66.79   68.13
                                                                                
                                                                                
                                                                                
                                                                                
                                                                                
                                                                                
BR Coef=-1 , 0 , 0 ,, 0 ,,,0.8,-1,,0,
WSPro=,,,, 1 ,,,, 0 ,,,, 0 ,,,,-1 ,-1 ,-1 , 0 , 0 , 0 , 0 , 0
Multiple Barrel Culv=2,10,10,36,0.013,0.4,1,8,1,38.8,38.75, 2,Culvert #1  , 0 ,32
   989.5  989.54 1000.56  1000.5
BC Culvert Barrel=1,Barrel #1,0
BC Culvert Barrel=2,Barrel #2,0
Culvert Bottom n=0.013
Multiple Barrel Culv=2,10,10,36,0.013,0.4,1,8,1,39,38.95, 2,Culvert #2  , 0 ,32
  1035.5  1035.5  1046.5  1046.5
BC Culvert Barrel=1,Barrel #1,0
BC Culvert Barrel=2,Barrel #2,0
Culvert Bottom n=0.013
BC Mult= 2 ,0,1030.15,0,1030.15
BC Mult= 2 ,1009.11,1508.37,1009.11,1508.37
BC Design=,, 0 ,, 0 ,,,,,,
BC Use User HTab Curves=0
BC User HTab FreeFlow(D)= 0

--- US278overBeaver.g06 (geometry) ---

Geom Title=Prop Cond_2-Double10x12
Program Version=6.50

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
River Reach=Beaver Dam Creek,Reach 1