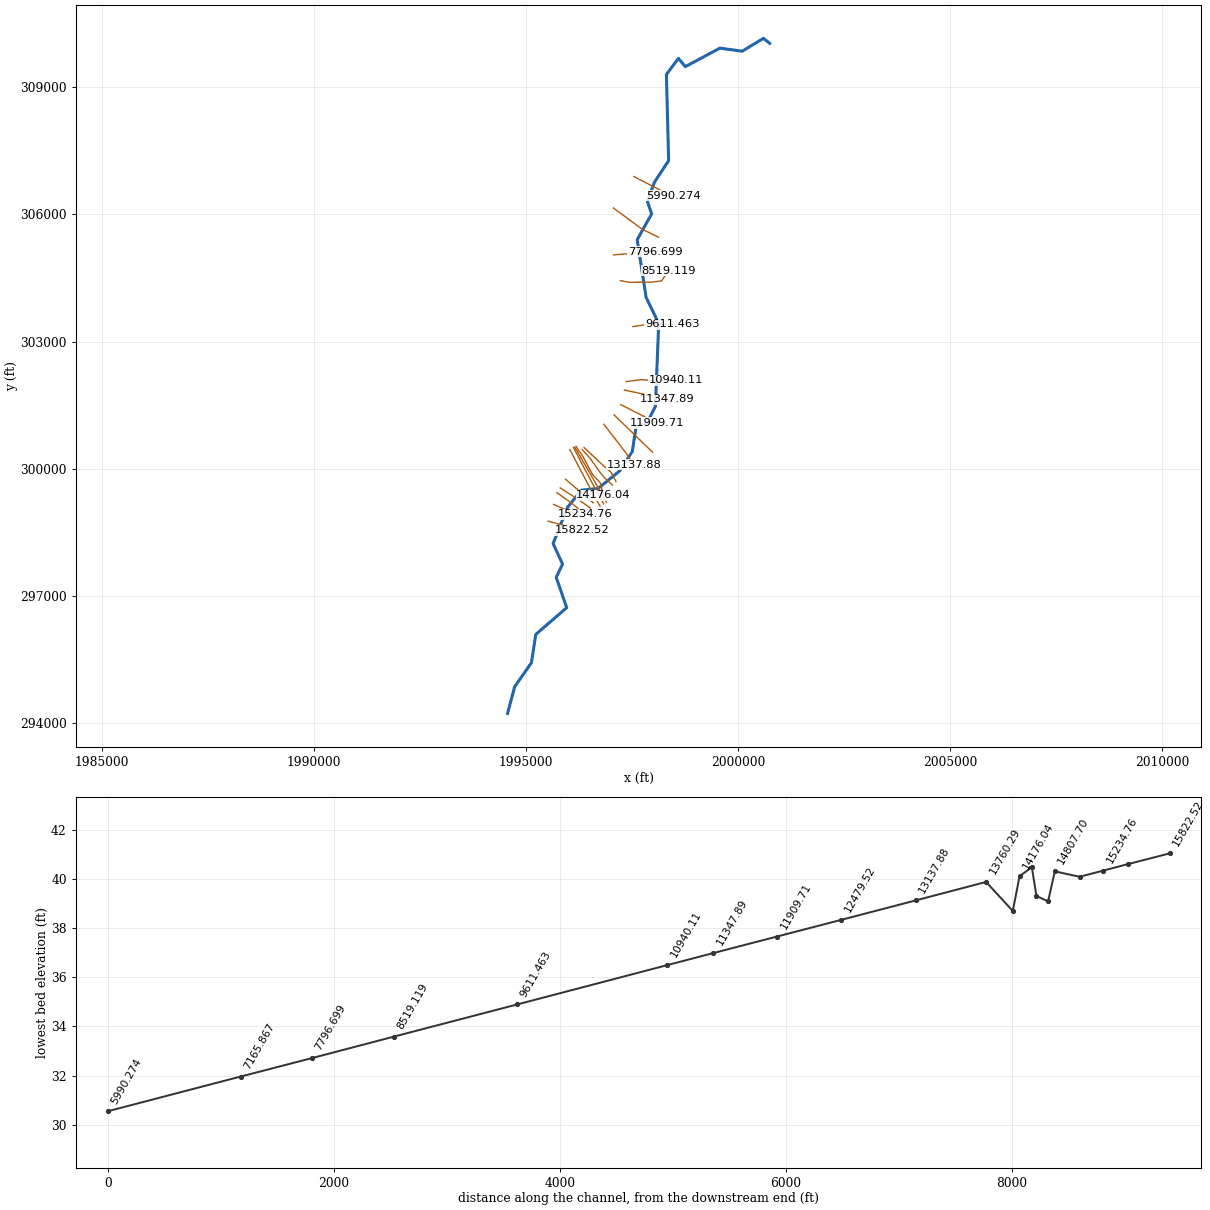
--- US 278_Beaver Dam Cr4_survey.prj (project) ---

Proj Title=US 278 Culvert Failure Beaver Dam Br.
Current Plan=p05
Default Exp/Contr=0.3,0.1
English Units
Geom File=g01
Geom File=g02
Geom File=g03
Geom File=g05
Flow File=f01
Plan File=p01
Plan File=p02
Plan File=p03
Plan File=p05
Y Axis Title=Elevation
X Axis Title(PF)=Main Channel Distance
X Axis Title(XS)=Station
BEGIN DESCRIPTION:
END DESCRIPTION:
DSS Export Rating Curves= 0
DSS Export Rating Curve Sorted= 0
DSS Export Volume Flow Curves= 0
DXF OffsetX= 0
DXF OffsetY= 0
DXF ScaleX= 1
DXF ScaleY= 10

--- US 278_Beaver Dam Cr4_survey.p05 (plan) ---

Plan Title=Proposed 160ft Flat Slab
Program Version=6.50
Short Identifier=Proposed 160ft Flat
Geom File=g05
Flow File=f01
Subcritical Flow
K Sum by GR= 0
Std Step Tol= 0.01
Critical Tol= 0.01
Num of Std Step Trials= 20
Max Error Tol= 0.3
Flow Tol Ratio= 0.001
Split Flow NTrial= 30
Split Flow Tol= 0.02
Split Flow Ratio= 0.02
Log Output Level= 0
Friction Slope Method= 1
Unsteady Friction Slope Method= 2
Unsteady Bridges Friction Slope Method= 1
Parabolic Critical Depth
Global Vel Dist= 0 , 0 , 0
Global Log Level= 0
CheckData=True
Encroach Param=-1 ,0,0, 0
Flow Ratio Tolerance=0.1
Flow Ratio Min Ratio=0.5
Flow Ratio Max Ratio=4
Flow Ratio Max Iterations= 10
Computation Interval=1MIN
Output Interval=1HOUR
Instantaneous Interval=1HOUR
Mapping Interval=1HOUR
Computation Time Step Use Courant=        0
Computation Time Step Use Time Series=    0
Computation Time Step Count To Double=0
Computation Time Step Max Doubling=0
Computation Time Step Max Halving=0
Computation Time Step Residence Courant=0
Run HTab= 0
Run UNet= 0
Run Sediment= 0
Run PostProcess= 0
Run WQNet= 0
Run RASMapper= 0
UNET Theta= 1
UNET Theta Warmup= 1
UNET ZTol= 0.02
UNET ZSATol= 0.02
UNET MxIter= 20
UNET Max Iter WO Improvement= 0
UNET MaxInSteps= 0
UNET DtIC= 0
UNET DtMin= 0
UNET MaxCRTS= 20
UNET WFStab= 2
UNET SFStab= 1
UNET WFX= 1
UNET SFX= 1
UNET Gravity=32.17405
UNET 1D Methodology=Finite Difference
UNET DSS MLevel= 4
UNET Pardiso=0
UNET DZMax Abort= 100
UNET Use Existing IB Tables=-1
UNET Froude Reduction=False
UNET Froude Limit= 0.8
UNET Froude Power= 4
UNET D1 Cores= 0
UNET WindReference=Eulerian
UNET WindDragFormulation=Hsu (1988)
UNET D2 Coriolis=0
UNET D2 Cores= 0
UNET D2 Theta= 1
UNET D2 Theta Warmup= 1
UNET D2 Z Tol= 0.01
UNET D2 Volume Tol= 0.01
UNET D2 Max Iterations= 20
UNET D2 Equation= 0
UNET D2 RampUpFraction=0.1
UNET D2 TimeSlices= 1
UNET D2 Turbulence Formulation=None
UNET D2 Eddy Viscosity=0.3
UNET D2 Transverse Eddy Viscosity=0.1
UNET D2 Smagorinsky Mixing=0.05
UNET D2 BCVolumeCheck=0
UNET D2 Cores=0
UNET D2 SolverType=PARDISO (Direct)
UNET D2 Minimum Iterations= 3
UNET D2 Maximum Iterations= 30
UNET D2 Restart Number= 10
UNET D2 Relaxation Coeff=1.3
UNET D2 SOR Precondition Iterations= 10
UNET D2 ILUT Maximum Fill= 8
UNET D2 ILUT Tolerance=1E-08
UNET D2 Convergence Tolerance=0.00001
PS Theta= 1
PS WS Tol= 0.01
PS Volume Tol= 0.01
PS Max Iterations= 20
PS Time Slices= 1
PS Iterate With 2D=0
PS Cores=0
UNET D1D2 MaxIter= 0
UNET D1D2 ZTol=0.01
UNET D1D2 QTol=0.1
UNET D1D2 MinQTol=1
Write IC File= 0
Write IC File at Fixed DateTime=0
Write IC File at Sim End=0
Echo Input=False
Echo Parameters=False
Echo Output=False
Write Detailed= 0
HDF Write Warmup=0
HDF Write Time Slices=0
HDF Flush=0
HDF Compression= 1
HDF Chunk Size= 1
HDF Spatial Parts= 1
HDF Use Max Rows=0
HDF Fixed Rows= 1
Calibration Method= 0
Calibration Iterations= 20
Calibration Max Change=0.05
Calibration Tolerance=0.2
Calibration Maximum=1.5
Calibration Minimum=0.5
Calibration Optimization Method= 1
WQ AD Non Conservative
WQ ULTIMATE=-1
WQ Max Comp Step=1HOUR
WQ Output Interval=15MIN
WQ Output Selected Increments= 0
WQ Create Restart=0
WQ Fixed Restart=0
WQ System Summary=0
WQ Write To DSS=0
Sorting and Armoring Iterations= 10
XS Update Threshold= 0.02
Bed Roughness Predictor= 0
Hydraulics Update Threshold= 0.02
Energy Slope Method= 1
Volume Change Method= 1
Sediment Retention Method= 0
Sediment TS Multiplier= 1
Warm Up Method= 0
XS Weighting Method= 0
Number of US Weighted Cross Sections= 1
Number of DS Weighted Cross Sections= 1
Upstream XS Weight=0
Main XS Weight=1
Downstream XS Weight=0
Number of DS XS's Weighted with US Boundary= 1
Upstream Boundary Weight= 1
Weight of XSs Associated with US Boundary= 0
Number of US XS's Weighted with DS Boundary= 1
Downstream Boundary Weight= 0.5
Weight of XSs Associated with DS Boundary= 0.5
Percentile Method= 0
Sediment Output Level= 3
Mass or Volume Output= 0
Output Increment Type= 1
Profile and TS Output Increment= 1
Transport Output Increment 1
XS Output Flag= 0
XS Output Increment= 10
Read HDF5 Sediment Hotstart= 0
Sediment Hotstart Type= 0
Write Gradation File= 0
Read Gradation Hotstart= 0
Write HDF5 File= 1
Write Binary Output= 1
Write DSS Sediment File= 0
DSS Sediment Output Type= 1
SV Curve= 0
Specific Gage Flag= 0
Subcell Erosion Methods= 0
Subcell Deposition Methods= 0
Advection Scheme= 1
Matrix Solver= 0
Implicit Weighting Factor= 1
Maximum Outer Loop Convergence Iterations= 5
Convergence Maximum Absolute= 0.001
Convergence RMSE= 0.0001
Grain Fractions Max Abs Error= 0.001
Max Subgrid Regions= 1
Max Subgrid Length Scale= 3.402823E+38
Initial Layer Thickness= 3
Min Layer Thickness= 0.1
Max Layer Thickness= 6
Number of Layers= 5

--- US 278_Beaver Dam Cr4_survey.p01 (plan) ---

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Plan Title=Existing Conditions
Short Identifier=Existing Conditions

--- US 278_Beaver Dam Cr4_survey.p02 (plan) ---

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Plan Title=Existing Conditions-2
Short Identifier=Existing Conditions-2
Geom File=g02
Flow File=f01

--- US 278_Beaver Dam Cr4_survey.p03 (plan) ---

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Plan Title=Natural Conditions-2
Short Identifier=Natural Conditions 2
Geom File=g03
Flow File=f01

--- US 278_Beaver Dam Cr4_survey.f01 (steady flow) ---

Flow Title=XMS Project Flow
Program Version=6.50
Number of Profiles= 7
Profile Names=50% AEP (2yr),10% AEP (10yr),4% AEP (25yr),2% AEP (50yr),1% AEP( 100yr),0.5% AEP (200yr),0.2% AEP (500yr)
River Rch & RM=Beaver Dam Branc,Reach 1         ,15822.52
     298     815    1160    1470    1790    2130    2600
Boundary for River Rch & Prof#=Beaver Dam Branc,Reach 1         , 1
Up Type= 0
Dn Type= 3
Dn Slope=0.0012
Boundary for River Rch & Prof#=Beaver Dam Branc,Reach 1         , 2
Up Type= 0
Dn Type= 3
Dn Slope=0.0012
Boundary for River Rch & Prof#=Beaver Dam Branc,Reach 1         , 3
Up Type= 0
Dn Type= 3
Dn Slope=0.0012
Boundary for River Rch & Prof#=Beaver Dam Branc,Reach 1         , 4
Up Type= 0
Dn Type= 3
Dn Slope=0.0012
Boundary for River Rch & Prof#=Beaver Dam Branc,Reach 1         , 5
Up Type= 0
Dn Type= 3
Dn Slope=0.0012
Boundary for River Rch & Prof#=Beaver Dam Branc,Reach 1         , 6
Up Type= 0
Dn Type= 3
Dn Slope=0.0012
Boundary for River Rch & Prof#=Beaver Dam Branc,Reach 1         , 7
Up Type= 0
Dn Type= 3
Dn Slope=0.0012
DSS Import GetInterval= 0
DSS Import GetPeak= 0
DSS Import FillOption= 0

--- US 278_Beaver Dam Cr4_survey.g05 (geometry) ---

Geom Title=Proposed-160ft Flat Slab_Geometry 2
Program Version=6.50

River Reach=Beaver Dam Branc,Reach 1
Reach XY= 30
      1994561.28       294231.89      1994728.91       294860.49
       1995124.4       295426.23      1995226.55       296094.11
       1995956.2        296724.3      1995708.47       297437.74
      1995857.76       297752.04      1995635.14       298233.96
      1995975.63       299093.05       1996306.4         299496.
      1996695.84       299534.74       1997207.5        299950.8
       1997502.5        300407.3       1997595.3        301017.7
       1997840.4        301063.8       1998046.6        301468.9
       1998125.3        303426.3       1997828.1         304041.
       1997617.2        305401.4      1997958.33       306007.63
       1997858.8       306300.97        1998025.         306758.
      1998359.06       307264.82      1998306.68       309297.29
      1998589.55       309677.07      1998751.93       309480.63
      1999569.11       309918.03      2000092.94       309844.69
      2000595.82       310148.52      2000742.49       310030.65

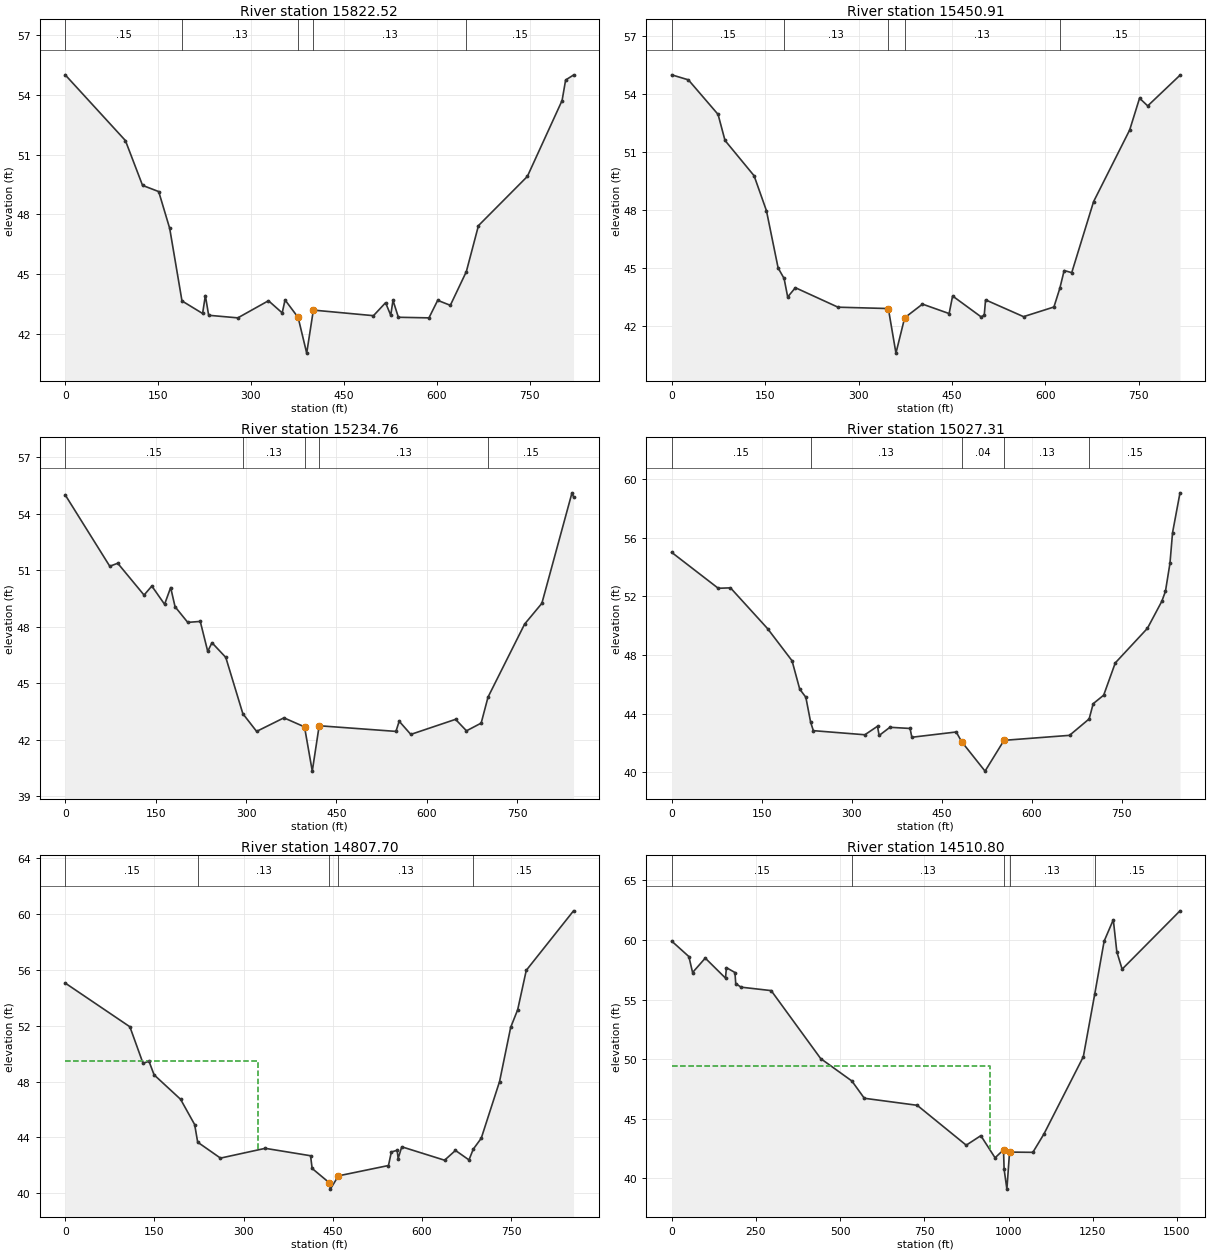
Type RM Length L Ch R = 1 ,15822.52,360,371.61,340
XS GIS Cut Line= 6
      1995520.95       298763.35      1996209.87       298577.81
      1996216.18        298576.1      1996218.86       298575.39
      1996261.44       298563.91      1996313.63       298549.86
#Sta/Elev= 30
       0      55   97.23    51.7  124.91   49.45  150.98   49.14  168.76   47.29
  188.59   43.65   221.9   43.02  226.34   43.92  231.67   42.93  278.75    42.8
  328.28   43.66  350.42   43.05  355.05    43.7  376.16   42.82     390   41.03
  400.75   43.19  497.83   42.91  517.37   43.56  525.73   42.93  529.36   43.68
  538.04   42.83  587.45    42.8  601.54   43.68  621.96   43.43   647.8   45.12
  667.39   47.43  746.36    49.9  802.44   53.71  808.16   54.74  820.93   54.99
#Mann= 5 ,-1,0
       0     .15       0  188.59     .13       0  376.16     .04       0
  400.75     .13       0   647.8     .15       0
Bank Sta=376.16,400.75
XS Rating Curve= 0 ,0
Exp/Cntr=0.3,0.1

Type RM Length L Ch R = 1 ,15450.91,190,216.15,160
XS GIS Cut Line= 6
      1995645.63       299159.32      1996043.66       298984.54
      1996048.88       298982.26      1996058.53       298978.01
      1996105.04        298957.6      1996392.75       298831.26
#Sta/Elev= 30
       0   55.01    26.8   54.75   74.47   52.96   85.61   51.61  132.31   49.78
  152.13   47.97  170.89      45  180.44   44.46  186.22    43.5  198.58   43.98
  267.01   42.97   347.8    42.9     360   40.59  373.99   42.42  402.59   43.13
  445.37   42.64  450.96   43.55  496.68   42.47  501.74   42.55  503.85   43.35
  564.82   42.48  613.59   42.98  623.08   43.95  630.03   44.87  642.18   44.76
  677.26   48.44  735.16   52.15  751.06    53.8  764.13    53.4  815.97   54.99
#Mann= 5 ,-1,0
       0     .15       0  180.44     .13       0   347.8     .04       0
  373.99     .13       0  623.08     .15       0
Bank Sta=347.8,373.99
XS Rating Curve= 0 ,0
Exp/Cntr=0.3,0.1

Type RM Length L Ch R = 1 ,15234.76,160,207.45,175
XS GIS Cut Line= 6
       1995723.1       299437.56      1996074.88       299187.75
      1996275.53       299017.88      1996279.15        299014.8
      1996346.01       298958.21      1996389.38       298921.48
#Sta/Elev= 30
       0      55   73.97   51.21   87.17   51.37  130.85   49.68  143.76   50.16
   164.9   49.19  174.98   50.08  182.31   49.06  203.35   48.23  224.11   48.28
  236.51   46.69  243.54   47.15  266.46   46.37  294.79   43.38  317.62   42.44
  362.97   43.16  397.13   42.68     410   40.33  421.44   42.74  548.87   42.44
  554.23   42.98  573.49   42.28  647.76   43.08  665.89   42.47  690.26   42.88
  701.63   44.26  762.39   48.14  790.97   49.24  840.99   55.11  843.54   54.89
#Mann= 5 ,-1,0
       0     .15       0  294.79     .13       0  397.13     .04       0
  421.44     .13       0  701.63     .15       0
Bank Sta=397.13,421.44
XS Rating Curve= 0 ,0
Exp/Cntr=0.3,0.1

Type RM Length L Ch R = 1 ,15027.31,195,219.6,175
BEGIN DESCRIPTION:
Upstream Limits of Survey
END DESCRIPTION:
XS GIS Cut Line= 6
      1995802.76       299546.81      1995818.88       299536.57
      1995819.54       299536.14      1995850.85       299516.26
       1996190.1        299300.7       1996508.8        299078.4
#Sta/Elev= 30
       0      55   77.67   52.55   98.05   52.58  159.88    49.8  200.65   47.61
  213.51   45.67  223.67   45.12  231.73   43.41   236.2   42.84  322.09   42.56
  343.16   43.14  345.87   42.51  363.84   43.07  397.45   42.99  400.41   42.39
  474.41   42.75  483.42   42.09  522.46   40.08   554.1   42.18  663.31   42.52
  696.02   43.64  702.76   44.68  720.26   45.26  739.58   47.46  793.18   49.82
  817.15   51.66  823.21   52.34  830.78   54.26  835.06   56.34  847.49   59.06
#Mann= 5 ,-1,0
       0     .15       0  231.73     .13       0  483.42     .04       0
   554.1     .13       0  696.02     .15       0
#XS Ineff= 2 , 0
       0     140   49.45               0
Permanent Ineff=
       F       F
Bank Sta=483.42,554.1
XS Rating Curve= 0 ,0
Exp/Cntr=0.5,0.3

Type RM Length L Ch R = 1 ,14807.70,54,59.38,42
XS GIS Cut Line= 6
       1995928.8        299751.4      1996262.01       299467.02
       1996349.5       299392.37      1996380.11       299366.23
      1996397.66       299351.27        1996579.        299196.5
#Sta/Elev= 30
       0   55.05  108.76   51.92  130.83   49.31  140.91   49.45  149.48   48.48
  194.01   46.73  217.69   44.92  222.76   43.66   261.1   42.52  336.42   43.22
  412.57   42.69  415.25   41.78  444.25   40.75  445.79    40.3  459.46   41.25
   543.6   41.99  548.45   42.96   558.2   43.08  559.89   42.49  565.94   43.33
  637.94   42.37  656.26   43.07  678.98   42.39  686.16   43.16  699.58   43.94
   730.4      48   749.1   51.88  760.87   53.14  775.31   55.96  854.79   60.22
#Mann= 5 ,-1,0
       0     .15       0  222.76     .13       0  444.25     .04       0
  459.46     .13       0  686.16     .15       0
#XS Ineff= 2 , 0
       0     325   49.45               0
Permanent Ineff=
       F       F
Bank Sta=444.25,459.46
XS Rating Curve= 0 ,0
Exp/Cntr=0.5,0.3

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
Type RM Length L Ch R = 1 ,14510.80,102,102.91,102
XS GIS Cut Line= 6
       1996029.1        300452.3       1996418.2        299711.1
       1996585.8        299387.3      1996615.49       299336.45
      1996628.47       299314.25       1996740.8        299121.9
#Sta/Elev= 30
       0   59.91   51.04   58.61   62.08   57.27   99.72   58.48  159.81    56.8
  162.47   57.68  187.82   57.27  190.19   56.34  205.92   56.04  295.44   55.75
  442.44   50.04     535   48.16   571.9   46.71  728.89   46.12  874.45   42.77
  917.82   43.57  960.07   41.71  985.11   42.38  986.94   40.75  995.15   39.08
 1003.09   42.19 1072.25   42.17 1105.17   43.71 1222.08    50.2 1255.96   55.46
 1283.83    59.9 1311.07    61.7 1321.52   59.01 1337.28   57.55 1509.07   62.45
#Mann= 5 ,-1,0
       0     .15       0     535     .13       0  985.11     .04       0
 1003.09     .13       0 1255.96     .15       0
#XS Ineff= 2 , 0
       0     945   49.45    1222       0   49.45
Permanent Ineff=
       F       F
Bank Sta=985.11,1003.09
XS Rating Curve= 0 ,0
Exp/Cntr=0.5,0.3

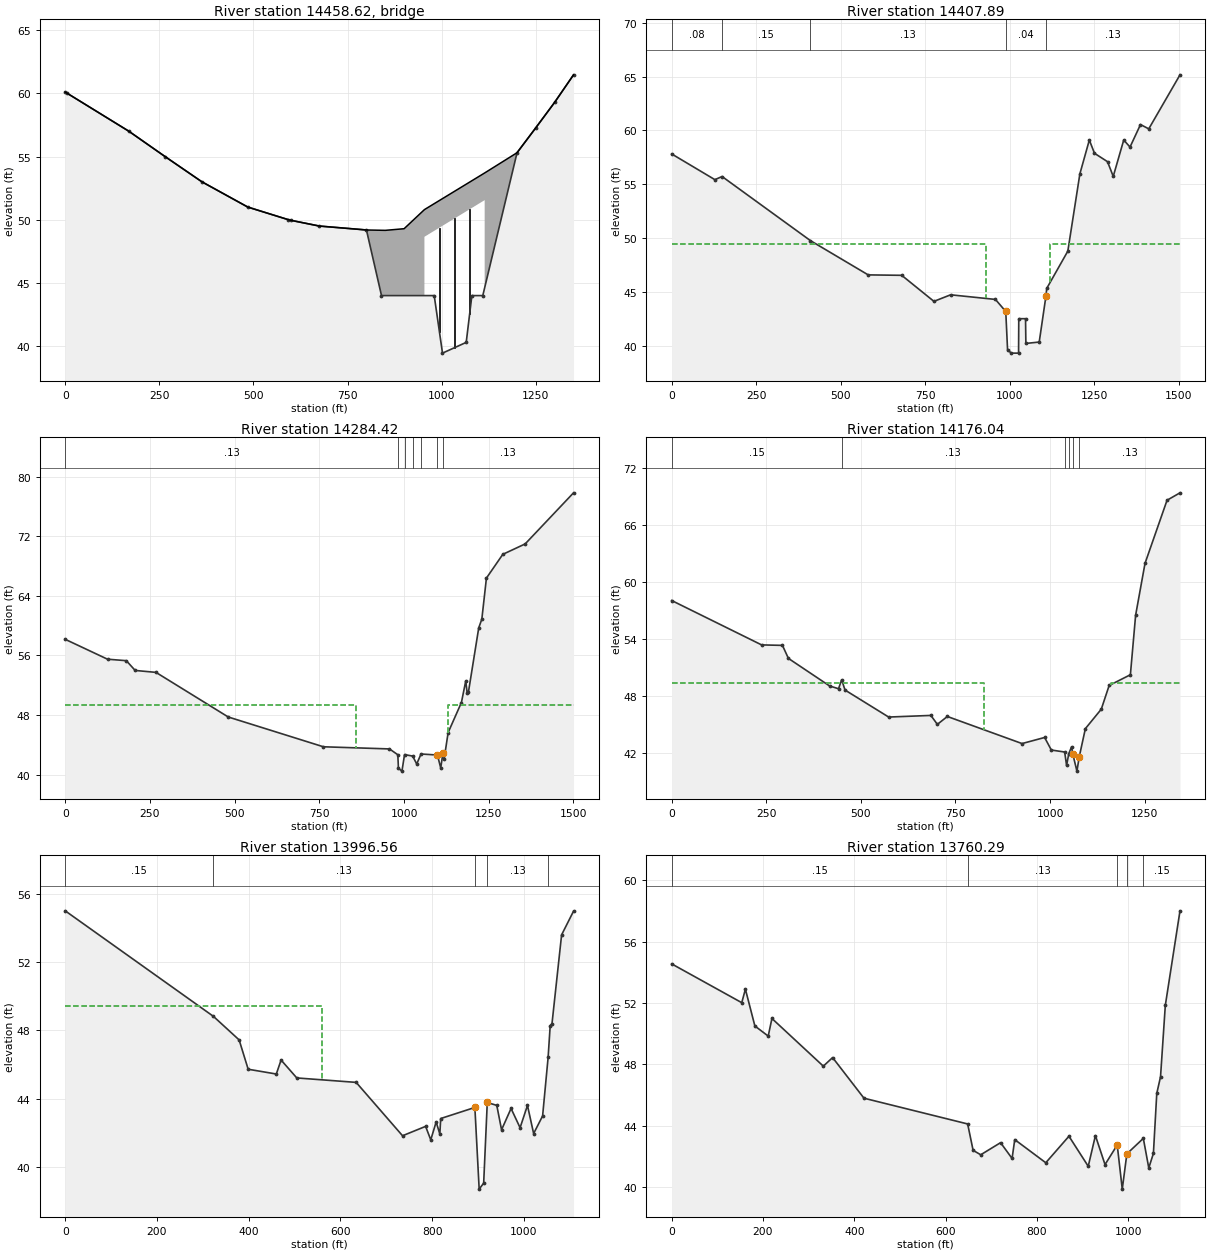
Type RM Length L Ch R = 3 ,14458.62,,,
Bridge Culvert--1,0,-1,-1, 0
Deck Dist Width WeirC Skew NumUp NumDn MinLoCord MaxHiCord MaxSubmerge Is_Ogee
30,42,2.6,0, 20, 20, , , 0.98, 0, 0,0,,
       0     5.3     169     265     363     485     593     600     675     800
     850     900     954     954    1114    1114    1200    1250    1300    1350
   60.09      60      57      55      53      51      50   49.95    49.5   49.19
   49.16   49.29    50.8    50.8    53.7    53.7    55.3   57.28   59.29   61.46
                                                                                
                           48.65   51.55
       0     5.3     169     265     363     485     593     600     675     800
     850     900     954     954    1114    1114    1200    1250    1300    1350
   60.09      60      57      55      53      51      50   49.95    49.5   49.19
   49.16   49.29    50.8    50.8    53.7    53.7    55.3   57.28   59.29   61.46
                                                                                
                           48.65   51.55
Pier Skew, UpSta & Num, DnSta & Num=  ,994, 2 ,994, 2 , 0 , 0 , 0 ,,
     1.7     1.7
       0      50
     1.7     1.7
       0      50
Pier Skew, UpSta & Num, DnSta & Num=  ,1034, 2 ,1034, 2 , 0 , 0 , 0 ,,
     1.7     1.7
       0      51
     1.7     1.7
       0      51
Pier Skew, UpSta & Num, DnSta & Num=  ,1074, 2 ,1074, 2 , 0 , 0 , 0 ,,
     1.7     1.7
       0      52
     1.7     1.7
       0      52
Abutment Skew #Up #Dn= , 2 , 2
     954     975
   50.65      40
     954     975
   50.65      40
Abutment Skew #Up #Dn= , 2 , 2
  1086.9    1114
      40   53.55
  1086.9    1114
      40   53.55
BR Coef=-1 , 0 , 0 ,, 0 ,,,0.8,-1,,0,
WSPro=,,,, 1 ,,,, 0 ,,,, 0 ,,,,-1 ,-1 ,-1 , 0 , 0 , 0 , 0 , 0
BR U #Sta/Elev= 20
       0   60.09     5.3      60     169      57     265      55     363      53
     485      51     593      50     600   49.95     675    49.5     800   49.19
     840      44     980      44    1002   39.45    1065    40.3    1080      44
    1109      44    1200    55.3    1250   57.28    1300   59.29    1350   61.46
BR U #Mann= 1
       0     .15
BR U Banks=980,1080
BR D #Sta/Elev= 20
       0   60.09     5.3      60     169      57     265      55     363      53
     485      51     593      50     600   49.95     675    49.5     800   49.19
     840      44     980      44    1002   39.45    1065    40.3    1080      44
    1109      44    1200    55.3    1250   57.28    1300   59.29    1350   61.46
BR D #Mann= 1
       0     .15
BR D Banks=980,1080
BC Design=,, 0 ,, 0 ,,,,,,
BC Use User HTab Curves=0
BC User HTab FreeFlow(D)= 0

Type RM Length L Ch R = 1 ,14407.89,25,41.16,25
XS GIS Cut Line= 6
       1996117.9        300498.9       1996334.9        300080.2
      1996478.53       299810.14      1996482.15       299803.35
       1996672.1        299444.4       1996826.3        299172.3
#Sta/Elev= 30
       0   57.81  127.79   55.42  149.21   55.71  410.75   49.75  581.45   46.57
  680.67   46.53  775.97   44.11  825.38   44.72  957.94   44.29  988.49   43.17
  993.88   39.58  1005.4    39.3  1026.4    39.3    1027    42.5    1047    42.5
    1048    40.2 1087.49   40.33 1107.52   44.63 1109.65   45.31 1172.17   48.78
 1207.79   55.96 1235.78    59.1 1250.98   57.87 1289.55   57.09 1306.53   55.72
 1337.53    59.1 1356.17   58.45 1387.13   60.54 1411.62   60.14 1504.03   65.16
#Mann= 5 ,-1,0
       0     .08       0  149.21     .15       0  410.75     .13       0
  988.49     .04       0 1107.52     .13       0
#XS Ineff= 2 , 0
       0     929    49.4    1120       0    49.4
Permanent Ineff=
       F       F
Bank Sta=988.49,1107.52
XS Rating Curve= 0 ,0
Exp/Cntr=0.5,0.3

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
Type RM Length L Ch R = 1 ,14284.42,85,108.38,65
XS GIS Cut Line= 6
       1996144.3        300506.6       1996178.5        300455.9
        1996520.        299864.2       1996797.7        299378.3
      1996798.91       299376.09       1996892.4        299206.4
#Sta/Elev= 30
       0   58.17  124.85    55.5  180.37    55.3  206.48   53.99  267.85   53.73
  481.14   47.74  761.96   43.74  957.09   43.45  981.63   42.67  983.48   40.85
  993.83   40.47 1001.48   42.69 1025.45   42.49  1037.4   41.43 1050.18   42.77
 1098.59   42.63 1108.29   40.89 1114.68   42.87 1118.47   42.13 1130.15   45.65
 1169.34   49.68  1182.2   52.59 1186.43    50.9 1189.96   51.05 1220.48   59.71
 1229.62   60.88 1243.17   66.39 1291.51   69.58 1357.53   70.98 1500.25   77.84
#Mann= 7 ,-1,0
       0     .13       0  981.63    .045       0 1001.48     .12       0
 1025.45    .045       0 1050.18     .12       0 1098.59     .04       0
 1114.68     .13       0
#XS Ineff= 2 , 0
       0     858    49.4    1130       0    49.4
Permanent Ineff=
       F       F
Bank Sta=1098.59,1114.68
XS Rating Curve= 0 ,0
Exp/Cntr=0.5,0.3

Type RM Length L Ch R = 1 ,14176.04,51.67,59.82,61.67
XS GIS Cut Line= 6
       1996175.6         300528.       1996340.1        300284.1
        1996567.        299861.2      1996729.96       299689.61
       1996744.7        299674.1       1996822.2        299372.8
#Sta/Elev= 30
       0   58.05  237.65   53.38  292.72   53.33  308.48   51.96  417.35   49.06
  440.92   48.77  449.27   49.71  458.09   48.63  573.38   45.79  684.92   45.96
   702.1   45.02  728.48   45.85  925.83      43  985.54   43.64 1003.21   42.32
 1038.49   42.11 1043.56    40.7 1049.46   41.95 1056.79   42.66 1060.07   41.88
 1070.89    40.1 1076.97    41.6 1093.21   44.57 1135.29   46.62 1156.02   49.11
 1212.16   50.24 1225.98    56.5 1250.83   61.96 1309.03    68.6 1343.26   69.38
#Mann= 6 ,-1,0
       0     .15       0  449.27     .13       0 1038.49    .045       0
 1049.46     .12       0 1060.07     .04       0 1076.97     .13       0
#XS Ineff= 2 , 0
       0     825    49.4    1161       0    49.4
Permanent Ineff=
       F       F
Bank Sta=1060.07,1076.97
XS Rating Curve= 0 ,0
Exp/Cntr=0.5,0.3

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
Type RM Length L Ch R = 1 ,13996.56,185,236.27,165
XS GIS Cut Line= 6
      1996319.63       300455.64      1996512.85       300237.43
      1996745.88       299910.39      1996859.57       299771.59
      1996994.95       299651.01      1997035.73        299614.7
#Sta/Elev= 30
       0   55.01  323.21   48.82  379.23   47.44  398.95   45.72  460.31   45.44
   470.7   46.26  504.94   45.21  634.38   44.95  735.52   41.82  785.82   42.37
  797.04   41.58   808.8   42.63  816.84   41.92  818.71   42.83  893.22   43.48
  902.59   38.69  912.41   39.04  920.26   43.77  941.01    43.6  951.41   42.17
  972.13   43.42   991.8   42.29  1007.9    43.6 1021.34   41.95 1040.91   42.98
 1052.92   46.41 1057.46   48.28 1061.36   48.39 1082.32    53.6 1108.34   54.99
#Mann= 5 ,-1,0
       0     .15       0  323.21     .13       0  893.22     .04       0
  920.26     .13       0 1052.92     .15       0
#XS Ineff= 2 , 0
       0     560    49.4    1090       0    49.4
Permanent Ineff=
       F       F
Bank Sta=893.22,920.26
XS Rating Curve= 0 ,0
Exp/Cntr=0.5,0.3

Type RM Length L Ch R = 1 ,13760.29,575,622.4,575
BEGIN DESCRIPTION:
Downstream Limits of Survey
END DESCRIPTION:
XS GIS Cut Line= 6
       1996365.5        300499.9       1996820.7        300072.3
      1996913.23       299993.58      1996921.56       299986.51
       1997006.2        299914.5        1997118.        299696.1
#Sta/Elev= 30
       0   54.56  153.51   52.03  161.49   52.91  182.25   50.51  211.47   49.85
  219.59      51  332.15   47.89  352.52   48.45  421.22    45.8  648.33   44.12
  660.25    42.4  676.95   42.11   720.4    42.9  745.63   41.87  751.45    43.1
  819.45   41.59  870.19   43.32  912.43   41.36  928.16   43.36  949.22   41.47
  975.92   42.75  986.97   39.87  997.05   42.17 1033.11   43.18 1045.05   41.25
 1055.19    42.2 1062.55   46.11  1070.8    47.2 1081.25   51.85 1113.43   58.02
#Mann= 5 ,-1,0
       0     .15       0  648.33     .13       0  975.92     .04       0
  997.05     .13       0 1033.11     .15       0
Bank Sta=975.92,997.05
XS Rating Curve= 0 ,0
Exp/Cntr=0.3,0.1

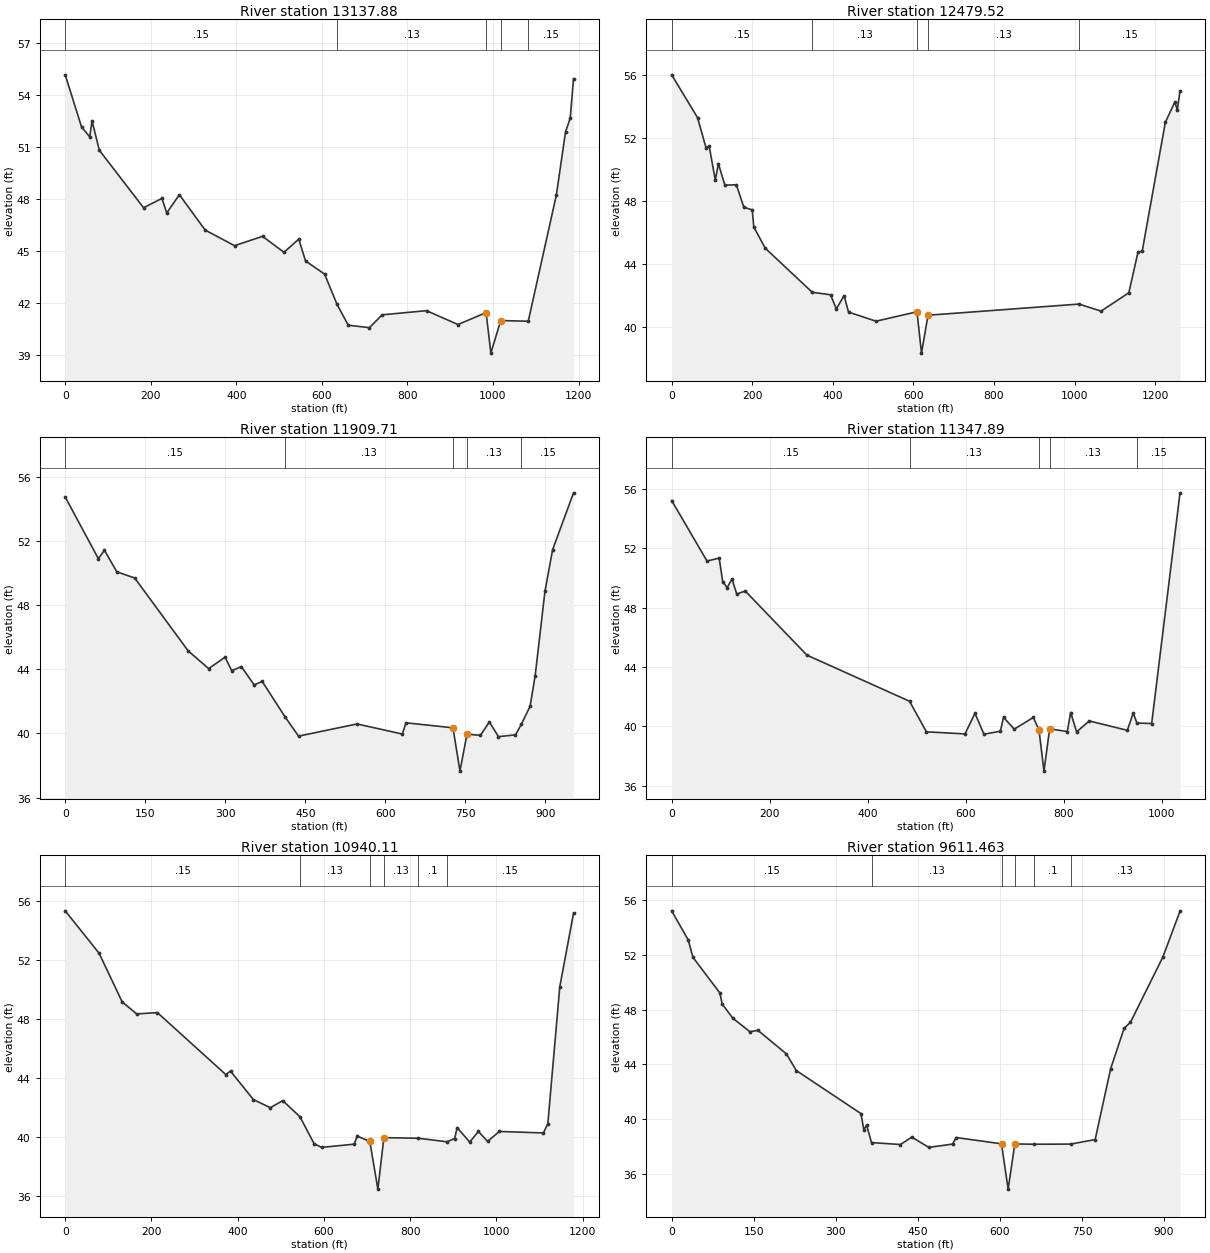
Type RM Length L Ch R = 1 ,13137.88,450,658.36,500
XS GIS Cut Line= 6
       1996830.9        301050.3       1997085.9        300721.2
       1997249.6        300505.3      1997253.11       300500.65
       1997396.3        300311.8       1997537.1        300095.4
#Sta/Elev= 30
       0   55.18   38.11   52.18   57.29    51.6    62.8   52.52   79.71   50.83
  183.19   47.51  226.27   48.05  237.33   47.21  266.86   48.26  327.21   46.22
  395.89   45.32   461.3   45.86   511.4   44.94  545.98    45.7  561.77   44.44
   606.4   43.68  635.47   41.93  661.66   40.73  711.25   40.59  740.86   41.33
  844.61   41.57  918.14   40.77  983.94   41.46     995   39.12 1018.06      41
 1082.42   40.96 1148.19   48.25 1169.56   51.89 1180.53   52.68 1188.27   54.96
#Mann= 5 ,-1,0
       0     .15       0  635.47     .13       0  983.94     .04       0
 1018.06     .13       0 1082.42     .15       0
Bank Sta=983.94,1018.06
XS Rating Curve= 0 ,0
Exp/Cntr=0.3,0.1

Type RM Length L Ch R = 1 ,12479.52,440,569.81,525
XS GIS Cut Line= 6
       1997073.1        301268.8      1997451.63       300901.83
      1997463.36       300890.44      1997519.47       300836.06
      1997552.45       300804.07      1997978.85       300390.69
#Sta/Elev= 30
       0   56.03   64.14   53.31   85.35   51.38   92.95   51.51  108.31   49.33
     116   50.38  131.96   49.01  160.51   49.04  179.09   47.61  199.97   47.44
  203.73   46.36  231.96   45.01  348.81    42.2  394.31   42.04  408.66   41.14
  427.87   41.99  438.89   40.94  507.09   40.36  608.81   40.96     620   38.33
  636.16   40.74 1011.12   41.45 1065.61      41 1134.52   42.17 1157.28   44.75
  1167.8   44.82 1225.15   53.01 1248.69    54.3 1254.74   53.81 1261.53      55
#Mann= 5 ,-1,0
       0     .15       0  348.81     .13       0  608.81     .04       0
  636.16     .13       0 1011.12     .15       0
Bank Sta=608.81,636.16
XS Rating Curve= 0 ,0
Exp/Cntr=0.3,0.1

Type RM Length L Ch R = 1 ,11909.71,520,561.82,565
XS GIS Cut Line= 6
       1997232.1        301511.1      1997729.16       301258.35
      1997770.86       301237.16      1997793.35       301225.71
       1997802.6       301221.02       1998081.5        301079.2
#Sta/Elev= 30
       0   54.73   62.15   50.89   73.52   51.41   96.76   50.07  130.35   49.68
  230.61   45.14  268.89   44.04  299.74   44.75  312.06   43.91  330.25   44.16
  354.24   43.02  369.25   43.24  411.77   41.05  437.39   39.83  547.11   40.59
  631.91   39.96  638.83   40.66  726.93   40.35     740   37.65  753.14   39.95
   778.2   39.88  795.21   40.71  812.16    39.8  844.09   39.91  854.95   40.56
  871.46   41.69  880.99    43.6   899.3   48.85  913.72   51.45   952.9   54.99
#Mann= 5 ,-1,0
       0     .15       0  411.77     .13       0  726.93     .04       0
  753.14     .13       0  854.95     .15       0
Bank Sta=726.93,753.14
XS Rating Curve= 0 ,0
Exp/Cntr=0.3,0.1

Type RM Length L Ch R = 1 ,11347.89,385,407.79,425
XS GIS Cut Line= 6
       1997316.3        301855.7       1997955.8       301718.15
      1998015.13        301705.4      1998112.53       301684.44
      1998130.76       301680.53       1998330.8        301637.5
#Sta/Elev= 30
       0   55.22   72.19   51.14   96.95   51.34  104.24   49.75  113.23   49.35
  123.08   49.93  132.79   48.92  150.25   49.12  276.03    44.8   485.6   41.69
  520.03   39.63  598.79   39.49  619.18   40.88  637.47   39.47  671.07   39.67
  677.43   40.61  699.27   39.81  738.34    40.6  749.84   39.75     760   36.98
  771.57   39.83  807.61   39.65  814.44   40.93  826.65   39.63  852.58   40.36
  930.19   39.73  942.22    40.9  949.72   40.22  979.87   40.19  1037.7   55.74
#Mann= 5 ,-1,0
       0     .15       0   485.6     .13       0  749.84     .04       0
  771.57     .13       0  949.72     .15       0
Bank Sta=749.84,771.57
XS Rating Curve= 0 ,0
Exp/Cntr=0.3,0.1

Type RM Length L Ch R = 1 ,10940.11,1310,1328.65,1320
XS GIS Cut Line= 6
       1997354.4        302054.8      1997646.65       302092.22
       1997705.8        302099.8       1998144.7        302075.5
       1998330.8        302074.7        1998529.        302089.4
#Sta/Elev= 30
       0   55.36   78.45   52.49  132.21   49.18  165.75   48.37  213.76   48.46
  372.28   44.26  383.32   44.49  436.45   42.56  475.66   42.01   504.3   42.49
   544.3    41.4  577.14   39.57  594.81   39.32  670.23   39.54  677.07   40.09
  706.34   39.72     725   36.49  738.89   39.98  818.76   39.94  885.31    39.7
  903.18   39.92  908.74   40.66     938   39.68  958.06    40.4  979.41   39.73
 1006.75    40.4  1108.8    40.3 1119.07   40.92 1146.81   50.21 1178.69    55.2
#Mann= 6 ,-1,0
       0     .15       0   544.3     .13       0  706.34     .04       0
  738.89     .13       0  818.76      .1       0  885.31     .15       0
Bank Sta=706.34,738.89
XS Rating Curve= 0 ,0
Exp/Cntr=0.3,0.1

Type RM Length L Ch R = 1 ,9611.463,1040,1092.34,1025
XS GIS Cut Line= 6
       1997514.1        303351.1      1997844.77       303401.28
      1997860.38       303403.65      1997861.31        303403.8
       1997865.3        303404.4       1998439.2        303403.5
#Sta/Elev= 30
       0   55.22   30.12    53.1   38.95   51.82   88.11   49.22   92.36   48.41
  111.68   47.38  142.93   46.39  157.69   46.49   209.7   44.77  227.86   43.55
  345.97   40.41  351.19   39.22  356.34   39.57  365.25   38.29  418.05   38.15
  438.92   38.69  469.95   37.94  513.39   38.18  520.03   38.66  602.87    38.2
     615   34.89  627.17   38.19  663.14   38.17  729.21   38.18  774.03   38.51
  802.38   43.69  826.99   46.64  838.63   47.08  897.76   51.84  929.12   55.19
#Mann= 6 ,-1,0
       0     .15       0  365.25     .13       0  602.87     .04       0
  627.17     .13       0  663.14      .1       0  729.21     .13       0
Bank Sta=602.87,627.17
XS Rating Curve= 0 ,0
Exp/Cntr=0.3,0.1

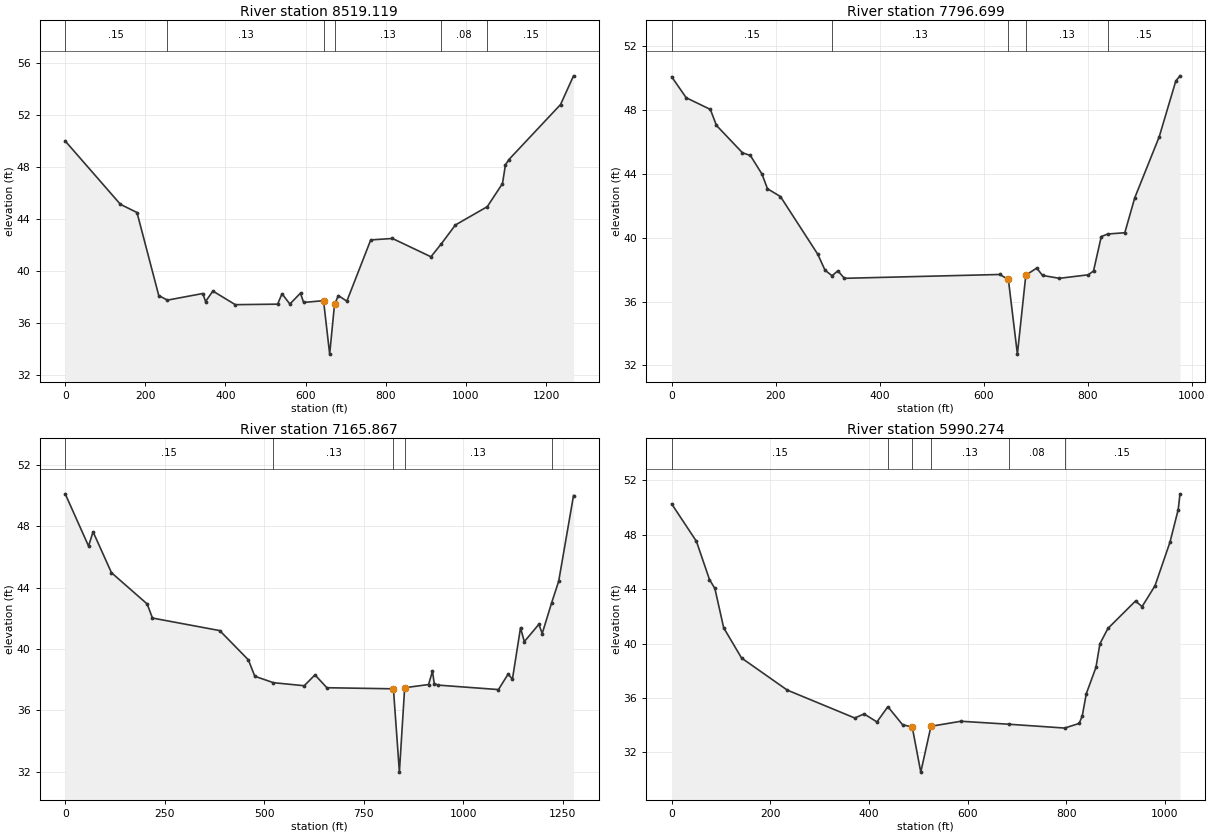
Type RM Length L Ch R = 1 ,8519.119,695,722.42,720
XS GIS Cut Line= 6
       1997218.8        304435.3       1997436.9        304395.4
       1997971.4        304401.2       1998191.4        304429.4
      1998252.29       304518.04       1998355.9        304668.9
#Sta/Elev= 30
       0      50   137.8   45.12  179.15   44.49  233.52   38.09   255.1   37.74
  343.39   38.25   350.3   37.63  368.51   38.44   424.5   37.39  530.03   37.43
  541.05   38.23  560.67   37.44  587.21   38.28  594.96   37.56  644.74    37.7
     660   33.58  672.11   37.42  681.89   38.09  702.87   37.66  762.51   42.38
  816.69   42.49  912.76   41.08   938.4   42.07  973.79   43.53 1053.31   44.94
 1091.29   46.72 1098.65   48.16 1107.27   48.57 1236.24   52.81  1268.6   55.02
#Mann= 6 ,-1,0
       0     .15       0   255.1     .13       0  644.74     .04       0
  672.11     .13       0   938.4     .08       0 1053.31     .15       0
Bank Sta=644.74,672.11
XS Rating Curve= 0 ,0
Exp/Cntr=0.3,0.1

Type RM Length L Ch R = 1 ,7796.699,675,630.83,490
XS GIS Cut Line= 6
       1997060.1        305042.8      1997076.98       305044.17
      1997213.65       305055.21      1997246.06       305057.84
      1997325.33       305064.24       1998034.7        305121.6
#Sta/Elev= 30
       0   50.05   27.95   48.74    74.4   48.01   86.14   47.01  136.15    45.3
  151.36   45.13  173.67   43.97  184.29   43.05  209.29   42.56  281.12   38.95
  294.92   37.96  308.48   37.61  319.72   37.92  332.13   37.45  631.03   37.69
  647.66   37.38     665   32.71  681.22   37.65  702.26   38.09   713.3   37.63
  745.87   37.45  801.35   37.67  811.44   37.91  826.34   40.06  838.73   40.22
  871.61    40.3  890.81   42.49  937.82    46.3  969.71   49.79  977.78   50.11
#Mann= 5 ,-1,0
       0     .15       0  308.48     .13       0  647.66     .04       0
  681.22     .13       0  838.73     .15       0
Bank Sta=647.66,681.22
XS Rating Curve= 0 ,0
Exp/Cntr=0.3,0.1

Type RM Length L Ch R = 1 ,7165.867,995,1175.59,1030
XS GIS Cut Line= 6
       1997055.4        306149.5      1997215.57       306031.39
      1997227.28       306022.74       1997227.6       306022.52
       1997740.2        305644.5        1998124.        305457.7
#Sta/Elev= 30
       0   50.13   58.71   46.72   70.01   47.65  116.29   44.98  205.99   42.94
  219.28   42.02  388.44    41.2  460.39   39.29  476.55   38.22  523.24    37.8
  600.81    37.6  627.82   38.31  657.71   37.47     825    37.4     840   31.96
  853.24   37.47  913.38   37.68  923.07   38.55  927.66   37.74  937.82   37.64
 1088.91   37.35 1113.34   38.36 1124.13   38.03 1144.44   41.38 1154.04   40.48
 1190.54   41.61 1198.98   41.01 1222.74   43.02 1240.38   44.42 1277.71   50.02
#Mann= 5 ,-1,0
       0     .15       0  523.24     .13       0     825     .04       0
  853.24     .13       0 1222.74     .15       0
Bank Sta=825,853.24
XS Rating Curve= 0 ,0
Exp/Cntr=0.3,0.1

Type RM Length L Ch R = 1 ,5990.274,0,0,0
XS GIS Cut Line= 6
       1997539.5        306890.7      1998138.86       306579.35
      1998225.69       306534.23      1998253.07       306520.02
        1998312.        306489.4        1998465.        306442.6
#Sta/Elev= 30
       0   50.27   50.16   47.52   76.64   44.71    87.6   44.05  105.45   41.16
  141.67   38.94  234.36   36.58  371.18   34.53  390.04   34.83  416.13   34.24
  438.29   35.36  467.99   34.04  487.73   33.86     505   30.55  525.64   33.92
  586.36   34.29  684.15   34.07  796.75   33.79  826.09   34.13  832.35   34.68
  840.58   36.32  860.12   38.25  868.18   39.99   884.3   41.11   940.3   43.13
  953.64   42.72  979.81   44.25 1010.14   47.45 1026.87   49.85 1030.51   51.01
#Mann= 6 ,-1,0
       0     .15       0  438.29     .13       0  487.73     .04       0
  525.64     .13       0  684.15     .08       0  796.75     .15       0
Bank Sta=487.73,525.64
XS Rating Curve= 0 ,0
Exp/Cntr=0.3,0.1
LCMann Table=0

Chan Stop Cuts=-1
Use User Specified Reach Order=0
Composite Channel Slope=5

--- US 278_Beaver Dam Cr4_survey.g01 (geometry) ---

Geom Title=Existing Geometry
Program Version=6.50

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
River Reach=Beaver Dam Branc,Reach 1

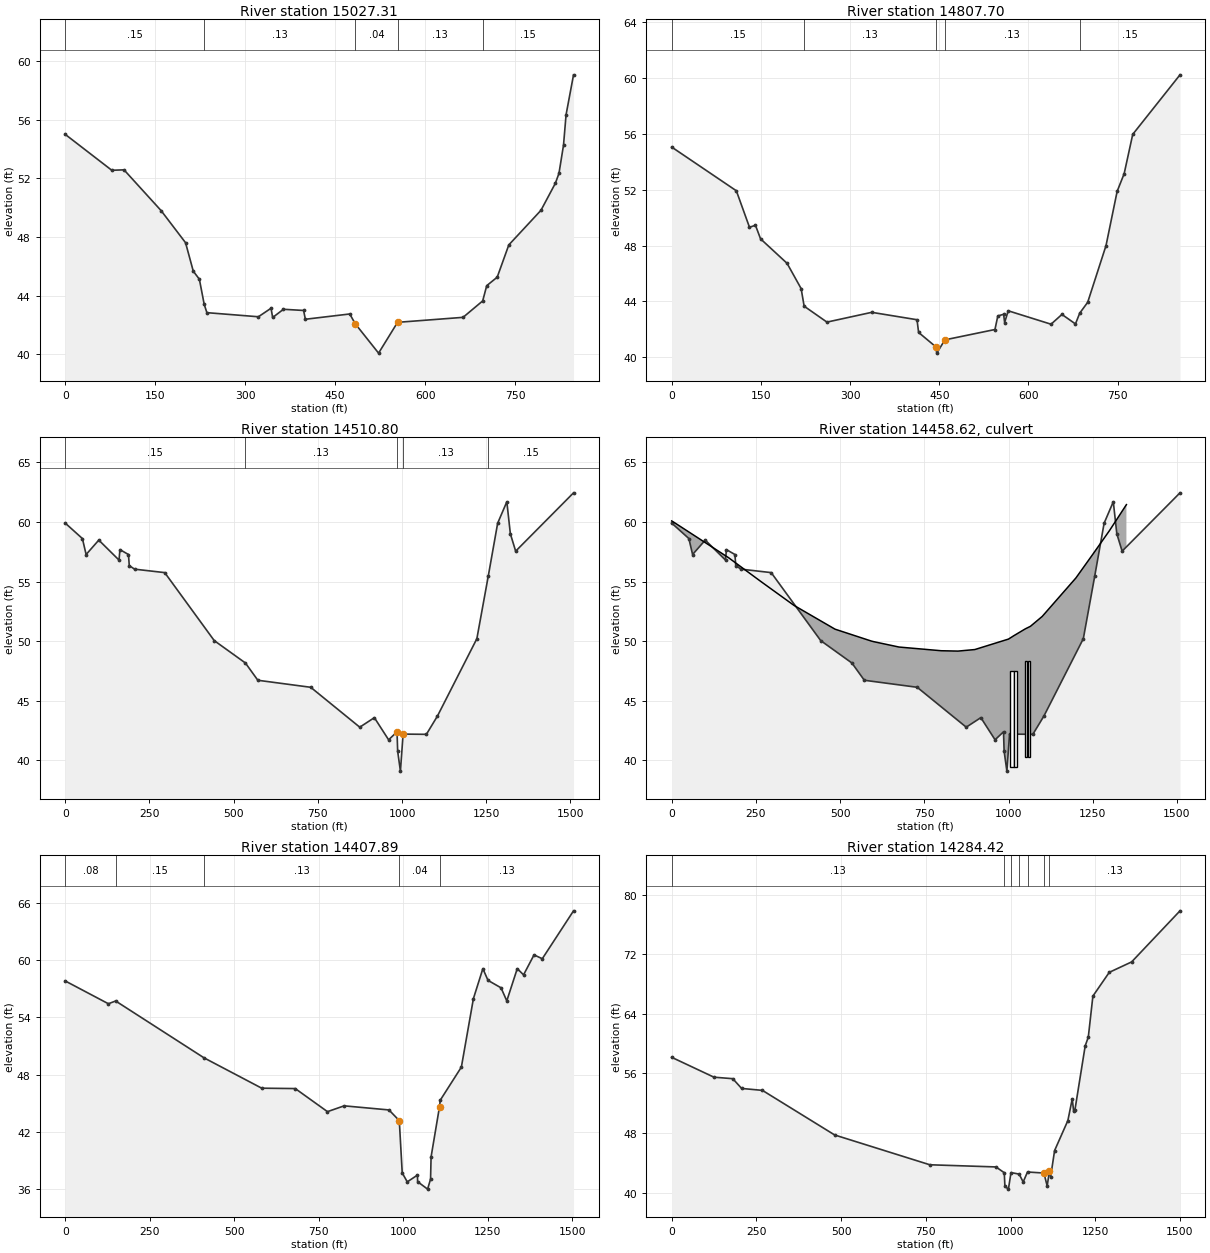
Type RM Length L Ch R = 1 ,15027.31,195,219.6,175
BEGIN DESCRIPTION:
Upstream Limits of Survey
END DESCRIPTION:
XS GIS Cut Line= 6
      1995802.76       299546.81      1995818.88       299536.57
      1995819.54       299536.14      1995850.85       299516.26
       1996190.1        299300.7       1996508.8        299078.4
#Sta/Elev= 30
       0      55   77.67   52.55   98.05   52.58  159.88    49.8  200.65   47.61
  213.51   45.67  223.67   45.12  231.73   43.41   236.2   42.84  322.09   42.56
  343.16   43.14  345.87   42.51  363.84   43.07  397.45   42.99  400.41   42.39
  474.41   42.75  483.42   42.09  522.46   40.08   554.1   42.18  663.31   42.52
  696.02   43.64  702.76   44.68  720.26   45.26  739.58   47.46  793.18   49.82
  817.15   51.66  823.21   52.34  830.78   54.26  835.06   56.34  847.49   59.06
#Mann= 5 ,-1,0
       0     .15       0  231.73     .13       0  483.42     .04       0
   554.1     .13       0  696.02     .15       0
Bank Sta=483.42,554.1
XS Rating Curve= 0 ,0
Exp/Cntr=0.3,0.1

Type RM Length L Ch R = 1 ,14807.70,270,296.9,210
XS GIS Cut Line= 6
       1995928.8        299751.4      1996262.01       299467.02
       1996349.5       299392.37      1996380.11       299366.23
      1996397.66       299351.27        1996579.        299196.5
#Sta/Elev= 30
       0   55.05  108.76   51.92  130.83   49.31  140.91   49.45  149.48   48.48
  194.01   46.73  217.69   44.92  222.76   43.66   261.1   42.52  336.42   43.22
  412.57   42.69  415.25   41.78  444.25   40.75  445.79    40.3  459.46   41.25
   543.6   41.99  548.45   42.96   558.2   43.08  559.89   42.49  565.94   43.33
  637.94   42.37  656.26   43.07  678.98   42.39  686.16   43.16  699.58   43.94
   730.4      48   749.1   51.88  760.87   53.14  775.31   55.96  854.79   60.22
#Mann= 5 ,-1,0
       0     .15       0  222.76     .13       0  444.25     .04       0
  459.46     .13       0  686.16     .15       0
Bank Sta=444.25,459.46
XS Rating Curve= 0 ,0
Exp/Cntr=0.3,0.1

Type RM Length L Ch R = 1 ,14510.80,102,102.91,102
XS GIS Cut Line= 6
       1996029.1        300452.3       1996418.2        299711.1
       1996585.8        299387.3      1996615.49       299336.45
      1996628.47       299314.25       1996740.8        299121.9
#Sta/Elev= 30
       0   59.91   51.04   58.61   62.08   57.27   99.72   58.48  159.81    56.8
  162.47   57.68  187.82   57.27  190.19   56.34  205.92   56.04  295.44   55.75
  442.44   50.04     535   48.16   571.9   46.71  728.89   46.12  874.45   42.77
  917.82   43.57  960.07   41.71  985.11   42.38  986.94   40.75  995.15   39.08
 1003.09   42.19 1072.25   42.17 1105.17   43.71 1222.08    50.2 1255.96   55.46
 1283.83    59.9 1311.07    61.7 1321.52   59.01 1337.28   57.55 1509.07   62.45
#Mann= 5 ,-1,0
       0     .15       0     535     .13       0  985.11     .04       0
 1003.09     .13       0 1255.96     .15       0
Bank Sta=985.11,1003.09
XS Rating Curve= 0 ,0
Exp/Cntr=0.3,0.1

Type RM Length L Ch R = 2 ,14458.62,,,
Bridge Culvert--1,0,-1,-1, 0
Deck Dist Width WeirC Skew NumUp NumDn MinLoCord MaxHiCord MaxSubmerge Is_Ogee
30,42,2.6,0, 21, 21, , , 0.98, 0, 0,0,,
       0     5.3     169     265     363     485     593     600     675     800
     850     900    1000    1015    1050    1065    1100    1200    1250    1300
    1350
   60.09      60      57      55      53      51      50   49.95    49.5   49.19
   49.16   49.29   50.17   50.44   51.03   51.24   52.07    55.3   57.28   59.29
   61.46
                                                                                
                                                                                
        
       0     5.3     169     265     363     485     593     600     675     800
     850     900    1000    1015    1050    1065    1100    1200    1250    1300
    1350
   60.09      60      57      55      53      51      50   49.95    49.5   49.19
   49.16   49.29   50.17   50.44   51.03   51.24   52.07    55.3   57.28   59.29
   61.46
                                                                                
                                                                                
        
BR Coef=-1 , 0 , 0 ,, 0 ,,,0.8,-1,,0,
WSPro=,,,, 1 ,,,, 0 ,,,, 0 ,,,,-1 ,-1 ,-1 , 0 , 0 , 0 , 0 , 0
Multiple Barrel Culv=2,8,10,42,0.013,0.4,1,8,1,39.45,39.4, 2,Culvert #1  , 0 ,30
  1010.4  1010.4  1021.4  1021.4
BC Culvert Barrel=1,Barrel #1,0
BC Culvert Barrel=2,Barrel #2,0
Culvert Bottom n=0.013
Multiple Barrel Culv=2,8,8,42,0.013,0.4,1,8,1,40.3,40.25, 2,Culvert #2  , 0 ,30
  1051.7  1051.7  1060.7  1060.7
BC Culvert Barrel=1,Barrel #1,0
BC Culvert Barrel=2,Barrel #2,0
Culvert Bottom n=0.013
BC Design=,, 0 ,, 0 ,,,,,,
BC Use User HTab Curves=0
BC User HTab FreeFlow(D)= 0

Type RM Length L Ch R = 1 ,14407.89,75,123.47,75
XS GIS Cut Line= 6
       1996117.9        300498.9       1996334.9        300080.2
      1996478.53       299810.14      1996482.15       299803.35
       1996672.1        299444.4       1996826.3        299172.3
#Sta/Elev= 30
       0   57.81  127.79   55.42  149.21   55.71  410.75   49.75  581.45   46.57
  680.67   46.53  775.97   44.11  825.38   44.72  957.94   44.29  988.49   43.17
  997.18   37.69 1012.06   36.75 1042.18   37.46  1042.7   36.77 1072.22   35.99
 1081.02   37.04 1082.55   39.37 1107.52   44.63 1109.65   45.31 1172.17   48.78
 1207.79   55.96 1235.78    59.1 1250.98   57.87 1289.55   57.09 1306.53   55.72
 1337.53    59.1 1356.17   58.45 1387.13   60.54 1411.62   60.14 1504.03   65.16
#Mann= 5 ,-1,0
       0     .08       0  149.21     .15       0  410.75     .13       0
  988.49     .04       0 1107.52     .13       0
Bank Sta=988.49,1107.52
XS Rating Curve= 0 ,0
Exp/Cntr=0.3,0.1

Type RM Length L Ch R = 1 ,14284.42,85,108.38,65
XS GIS Cut Line= 6
       1996144.3        300506.6       1996178.5        300455.9
        1996520.        299864.2       1996797.7        299378.3
      1996798.91       299376.09       1996892.4        299206.4
#Sta/Elev= 30
       0   58.17  124.85    55.5  180.37    55.3  206.48   53.99  267.85   53.73
  481.14   47.74  761.96   43.74  957.09   43.45  981.63   42.67  983.48   40.85
  993.83   40.47 1001.48   42.69 1025.45   42.49  1037.4   41.43 1050.18   42.77
 1098.59   42.63 1108.29   40.89 1114.68   42.87 1118.47   42.13 1130.15   45.65
 1169.34   49.68  1182.2   52.59 1186.43    50.9 1189.96   51.05 1220.48   59.71
 1229.62   60.88 1243.17   66.39 1291.51   69.58 1357.53   70.98 1500.25   77.84
#Mann= 7 ,-1,0
       0     .13       0  981.63    .045       0 1001.48     .12       0
 1025.45    .045       0 1050.18     .12       0 1098.59     .04       0
 1114.68     .13       0
Bank Sta=1098.59,1114.68
XS Rating Curve= 0 ,0
Exp/Cntr=0.3,0.1