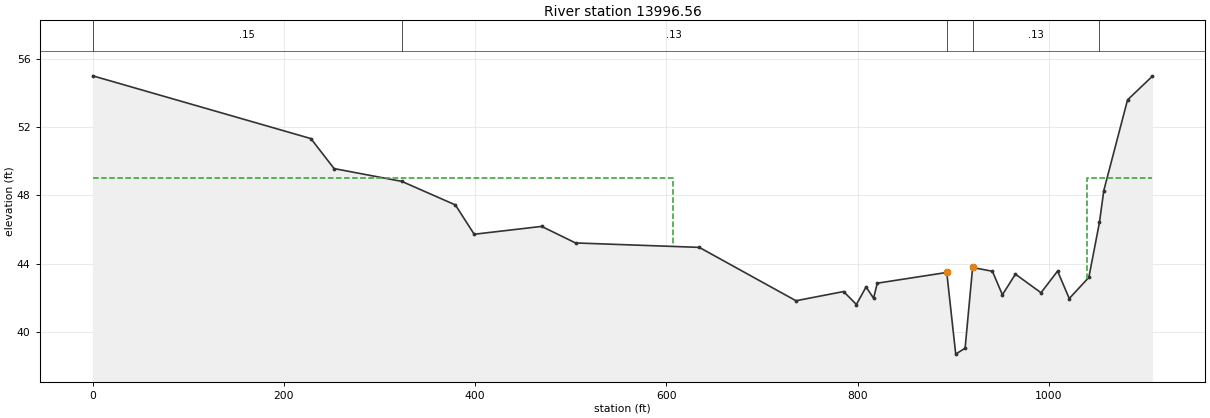
HEC-RAS study US 278_Beaver Dam Cr4_survey.prj: US 278 Culvert Failure Beaver Dam Br.

--- US 278_Beaver Dam Cr4_survey.g02 (geometry) --- (continued)

Type RM Length L Ch R = 1 ,13996.56,185,236.27,165
XS GIS Cut Line= 6
      1996319.63       300455.64      1996512.85       300237.43
      1996745.88       299910.39      1996859.57       299771.59
      1996994.95       299651.01      1997035.73        299614.7
#Sta/Elev= 30
       0   55.01  228.11   51.33  252.42   49.57  323.21   48.82  379.23   47.44
  398.95   45.72  469.51   46.18  504.94   45.21  634.38   44.95  735.52   41.82
  785.33   42.36   798.7    41.6   808.8   42.63  816.65   41.97  820.55   42.85
  893.22   43.48  902.59   38.69  912.41   39.04  920.26   43.77  940.97   43.55
  951.41   42.17  965.04   43.38   991.8   42.29 1009.14   43.56 1021.34   41.95
 1041.82   43.19 1052.92   46.41 1057.46   48.28 1082.32    53.6 1108.34   54.99
#Mann= 5 ,-1,0
       0     .15       0  323.21     .13       0  893.22     .04       0
  920.26     .13       0 1052.92     .15       0
#XS Ineff= 2 , 0
       0     607      49    1040       0      49
Permanent Ineff=
       F       F
Bank Sta=893.22,920.26
XS Rating Curve= 0 ,0
Exp/Cntr=0.3,0.1

--- US 278_Beaver Dam Cr4_survey.g03 (geometry) ---

Geom Title=Natural Geometry 2
Program Version=6.50

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
River Reach=Beaver Dam Branc,Reach 1

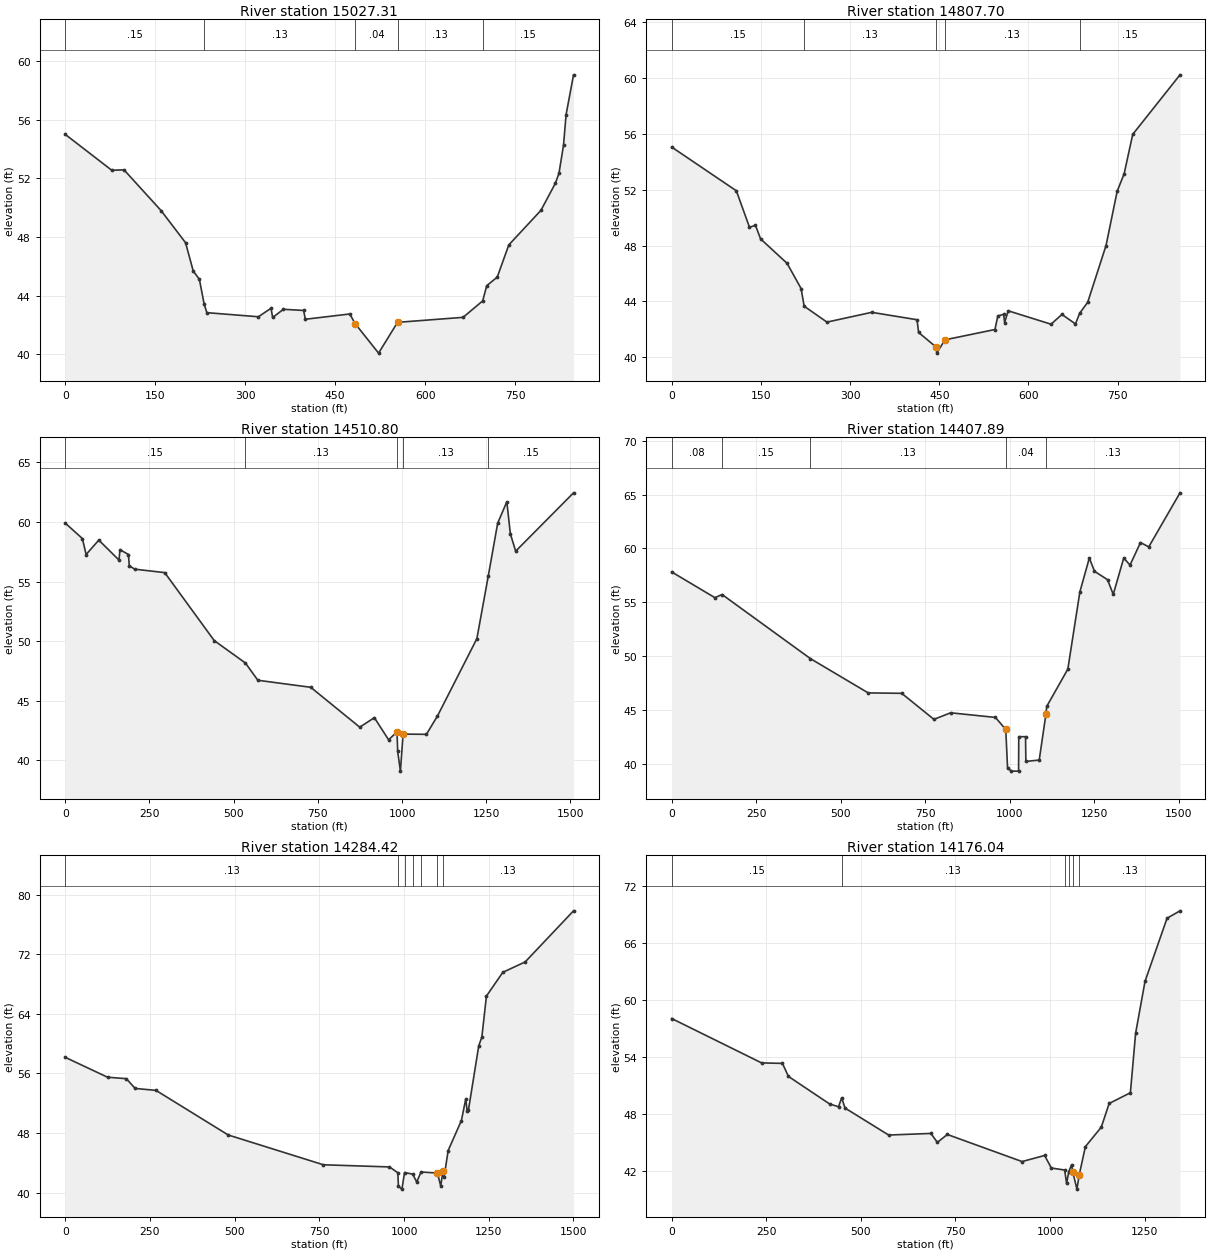
Type RM Length L Ch R = 1 ,15027.31,195,219.6,175
BEGIN DESCRIPTION:
Upstream Limits of Survey
END DESCRIPTION:
XS GIS Cut Line= 6
      1995802.76       299546.81      1995818.88       299536.57
      1995819.54       299536.14      1995850.85       299516.26
       1996190.1        299300.7       1996508.8        299078.4
#Sta/Elev= 30
       0      55   77.67   52.55   98.05   52.58  159.88    49.8  200.65   47.61
  213.51   45.67  223.67   45.12  231.73   43.41   236.2   42.84  322.09   42.56
  343.16   43.14  345.87   42.51  363.84   43.07  397.45   42.99  400.41   42.39
  474.41   42.75  483.42   42.09  522.46   40.08   554.1   42.18  663.31   42.52
  696.02   43.64  702.76   44.68  720.26   45.26  739.58   47.46  793.18   49.82
  817.15   51.66  823.21   52.34  830.78   54.26  835.06   56.34  847.49   59.06
#Mann= 5 ,-1,0
       0     .15       0  231.73     .13       0  483.42     .04       0
   554.1     .13       0  696.02     .15       0
Bank Sta=483.42,554.1
XS Rating Curve= 0 ,0
Exp/Cntr=0.3,0.1

Type RM Length L Ch R = 1 ,14807.70,54,59.38,42
XS GIS Cut Line= 6
       1995928.8        299751.4      1996262.01       299467.02
       1996349.5       299392.37      1996380.11       299366.23
      1996397.66       299351.27        1996579.        299196.5
#Sta/Elev= 30
       0   55.05  108.76   51.92  130.83   49.31  140.91   49.45  149.48   48.48
  194.01   46.73  217.69   44.92  222.76   43.66   261.1   42.52  336.42   43.22
  412.57   42.69  415.25   41.78  444.25   40.75  445.79    40.3  459.46   41.25
   543.6   41.99  548.45   42.96   558.2   43.08  559.89   42.49  565.94   43.33
  637.94   42.37  656.26   43.07  678.98   42.39  686.16   43.16  699.58   43.94
   730.4      48   749.1   51.88  760.87   53.14  775.31   55.96  854.79   60.22
#Mann= 5 ,-1,0
       0     .15       0  222.76     .13       0  444.25     .04       0
  459.46     .13       0  686.16     .15       0
Bank Sta=444.25,459.46
XS Rating Curve= 0 ,0
Exp/Cntr=0.3,0.1

Type RM Length L Ch R = 1 ,14510.80,102,102.91,102
XS GIS Cut Line= 6
       1996029.1        300452.3       1996418.2        299711.1
       1996585.8        299387.3      1996615.49       299336.45
      1996628.47       299314.25       1996740.8        299121.9
#Sta/Elev= 30
       0   59.91   51.04   58.61   62.08   57.27   99.72   58.48  159.81    56.8
  162.47   57.68  187.82   57.27  190.19   56.34  205.92   56.04  295.44   55.75
  442.44   50.04     535   48.16   571.9   46.71  728.89   46.12  874.45   42.77
  917.82   43.57  960.07   41.71  985.11   42.38  986.94   40.75  995.15   39.08
 1003.09   42.19 1072.25   42.17 1105.17   43.71 1222.08    50.2 1255.96   55.46
 1283.83    59.9 1311.07    61.7 1321.52   59.01 1337.28   57.55 1509.07   62.45
#Mann= 5 ,-1,0
       0     .15       0     535     .13       0  985.11     .04       0
 1003.09     .13       0 1255.96     .15       0
Bank Sta=985.11,1003.09
XS Rating Curve= 0 ,0
Exp/Cntr=0.3,0.1

Type RM Length L Ch R = 1 ,14407.89,25,41.16,25
XS GIS Cut Line= 6
       1996117.9        300498.9       1996334.9        300080.2
      1996478.53       299810.14      1996482.15       299803.35
       1996672.1        299444.4       1996826.3        299172.3
#Sta/Elev= 30
       0   57.81  127.79   55.42  149.21   55.71  410.75   49.75  581.45   46.57
  680.67   46.53  775.97   44.11  825.38   44.72  957.94   44.29  988.49   43.17
  993.88   39.58  1005.4    39.3  1026.4    39.3    1027    42.5    1047    42.5
    1048    40.2 1087.49   40.33 1107.52   44.63 1109.65   45.31 1172.17   48.78
 1207.79   55.96 1235.78    59.1 1250.98   57.87 1289.55   57.09 1306.53   55.72
 1337.53    59.1 1356.17   58.45 1387.13   60.54 1411.62   60.14 1504.03   65.16
#Mann= 5 ,-1,0
       0     .08       0  149.21     .15       0  410.75     .13       0
  988.49     .04       0 1107.52     .13       0
Bank Sta=988.49,1107.52
XS Rating Curve= 0 ,0
Exp/Cntr=0.3,0.1

Type RM Length L Ch R = 1 ,14284.42,85,108.38,65
XS GIS Cut Line= 6
       1996144.3        300506.6       1996178.5        300455.9
        1996520.        299864.2       1996797.7        299378.3
      1996798.91       299376.09       1996892.4        299206.4
#Sta/Elev= 30
       0   58.17  124.85    55.5  180.37    55.3  206.48   53.99  267.85   53.73
  481.14   47.74  761.96   43.74  957.09   43.45  981.63   42.67  983.48   40.85
  993.83   40.47 1001.48   42.69 1025.45   42.49  1037.4   41.43 1050.18   42.77
 1098.59   42.63 1108.29   40.89 1114.68   42.87 1118.47   42.13 1130.15   45.65
 1169.34   49.68  1182.2   52.59 1186.43    50.9 1189.96   51.05 1220.48   59.71
 1229.62   60.88 1243.17   66.39 1291.51   69.58 1357.53   70.98 1500.25   77.84
#Mann= 7 ,-1,0
       0     .13       0  981.63    .045       0 1001.48     .12       0
 1025.45    .045       0 1050.18     .12       0 1098.59     .04       0
 1114.68     .13       0
Bank Sta=1098.59,1114.68
XS Rating Curve= 0 ,0
Exp/Cntr=0.3,0.1

Type RM Length L Ch R = 1 ,14176.04,51.67,59.82,61.67
XS GIS Cut Line= 6
       1996175.6         300528.       1996340.1        300284.1
        1996567.        299861.2      1996729.96       299689.61
       1996744.7        299674.1       1996822.2        299372.8
#Sta/Elev= 30
       0   58.05  237.65   53.38  292.72   53.33  308.48   51.96  417.35   49.06
  440.92   48.77  449.27   49.71  458.09   48.63  573.38   45.79  684.92   45.96
   702.1   45.02  728.48   45.85  925.83      43  985.54   43.64 1003.21   42.32
 1038.49   42.11 1043.56    40.7 1049.46   41.95 1056.79   42.66 1060.07   41.88
 1070.89    40.1 1076.97    41.6 1093.21   44.57 1135.29   46.62 1156.02   49.11
 1212.16   50.24 1225.98    56.5 1250.83   61.96 1309.03    68.6 1343.26   69.38
#Mann= 6 ,-1,0
       0     .15       0  449.27     .13       0 1038.49    .045       0
 1049.46     .12       0 1060.07     .04       0 1076.97     .13       0
Bank Sta=1060.07,1076.97
XS Rating Curve= 0 ,0
Exp/Cntr=0.3,0.1

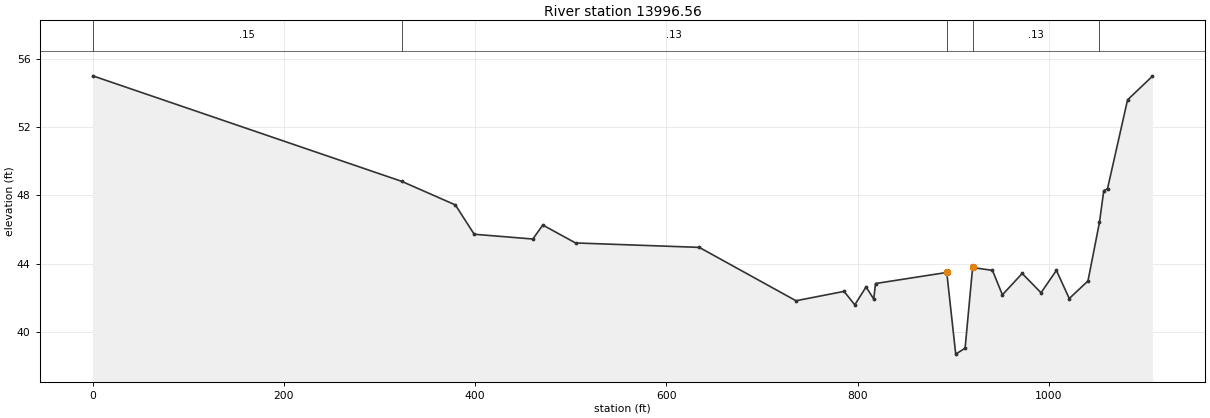
Type RM Length L Ch R = 1 ,13996.56,185,236.27,165
XS GIS Cut Line= 6
      1996319.63       300455.64      1996512.85       300237.43
      1996745.88       299910.39      1996859.57       299771.59
      1996994.95       299651.01      1997035.73        299614.7
#Sta/Elev= 30
       0   55.01  323.21   48.82  379.23   47.44  398.95   45.72  460.31   45.44
   470.7   46.26  504.94   45.21  634.38   44.95  735.52   41.82  785.82   42.37
  797.04   41.58   808.8   42.63  816.84   41.92  818.71   42.83  893.22   43.48
  902.59   38.69  912.41   39.04  920.26   43.77  941.01    43.6  951.41   42.17
  972.13   43.42   991.8   42.29  1007.9    43.6 1021.34   41.95 1040.91   42.98
 1052.92   46.41 1057.46   48.28 1061.36   48.39 1082.32    53.6 1108.34   54.99
#Mann= 5 ,-1,0
       0     .15       0  323.21     .13       0  893.22     .04       0
  920.26     .13       0 1052.92     .15       0
Bank Sta=893.22,920.26
XS Rating Curve= 0 ,0
Exp/Cntr=0.3,0.1